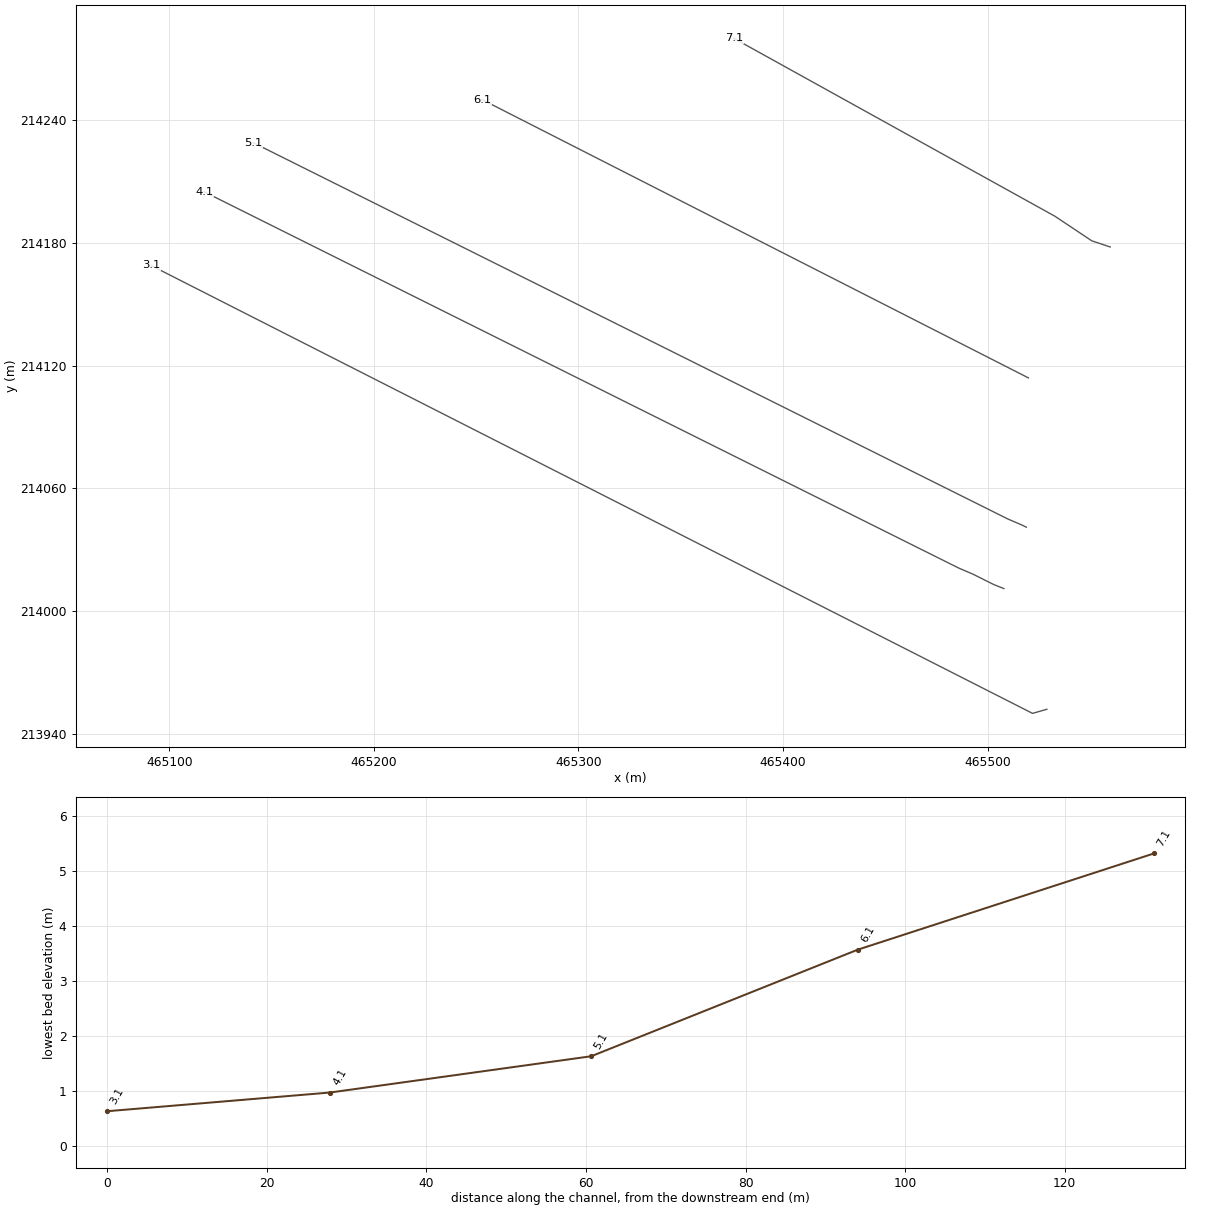
HEC-RAS study Lucky_global_v2.prj: Lucky_global_v2

--- Lucky_global_v2.g01 (geometry) --- (continued)

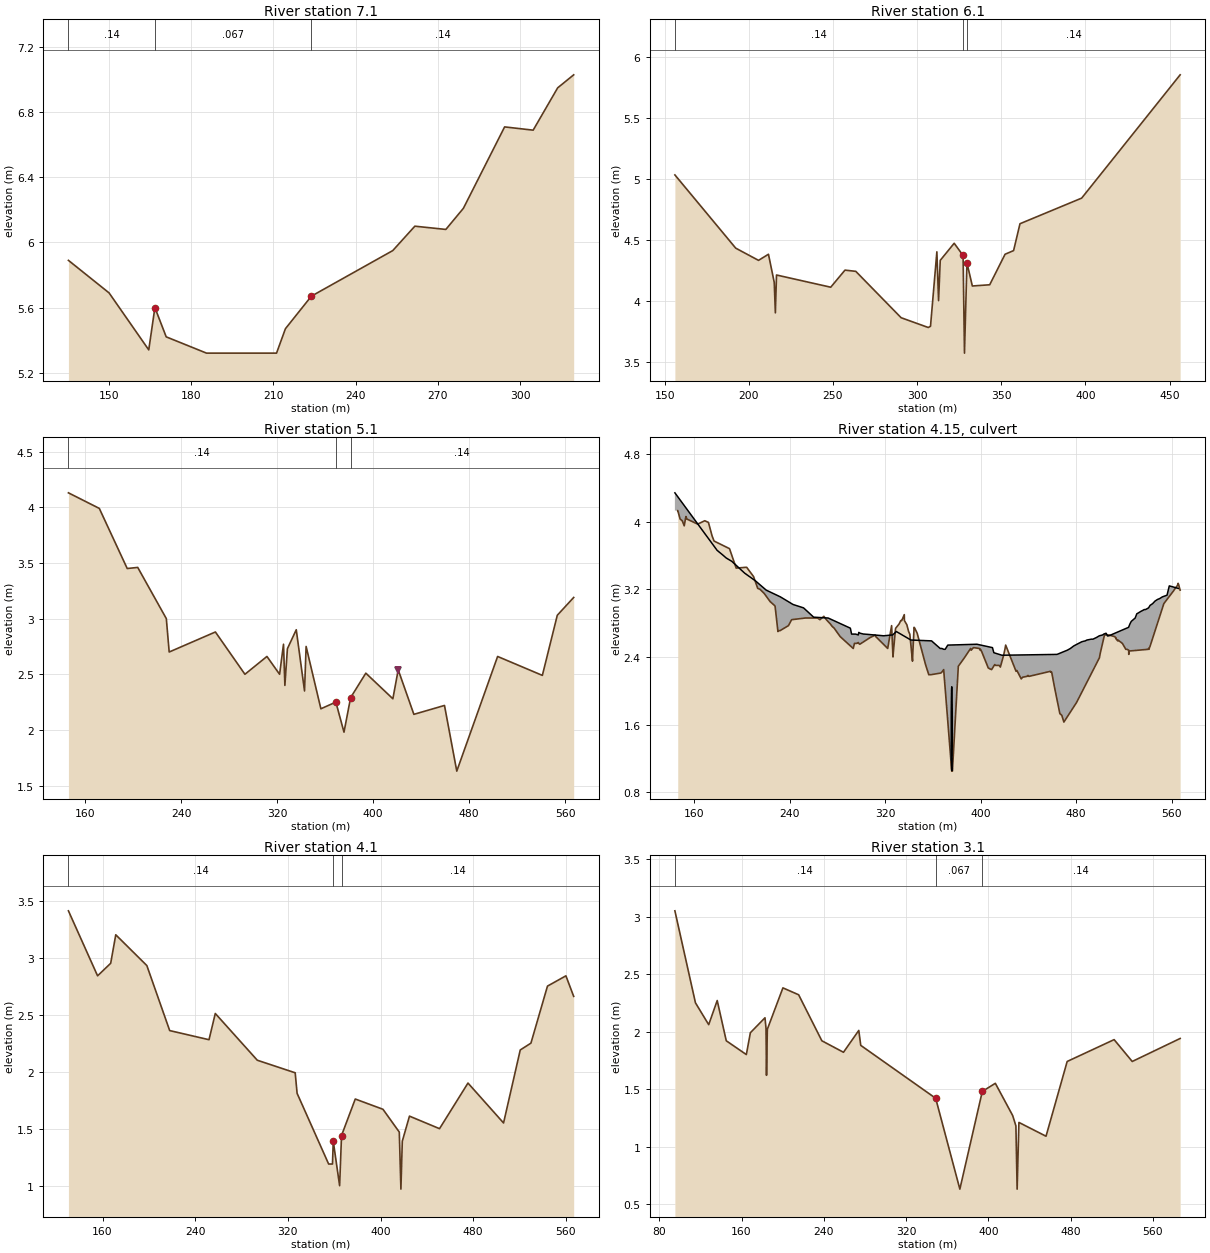
Type RM Length L Ch R = 1 ,7.1     ,37.105,37.105,37.105
XS GIS Cut Line= 4
         465560.         214178.         465551.         214181.
         465533.         214193.         465376.         214280.
#Sta/Elev= 17
  135.26    5.89  150.09    5.69  164.56    5.34   166.8     5.6  170.92    5.42
  185.62    5.32  211.17    5.32  214.41    5.47  223.88    5.67  253.56    5.95
  261.62     6.1  272.92    6.08  279.33    6.21  294.36    6.71  304.77    6.69
  313.71    6.95  319.55    7.03
#Mann= 3 , 0 , 0
  135.26     .14       0   166.8    .067       0  223.88     .14       0
Bank Sta=166.8,223.88
XS Rating Curve= 0 ,0
Exp/Cntr=0.3,0.1

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
Type RM Length L Ch R = 1 ,6.1     ,33.425,33.425,33.425
XS GIS Cut Line= 2
         465520.         214114.         465253.         214250.
#Sta/Elev= 27
  156.11    5.03  192.25    4.43  205.79    4.33   211.7    4.38  215.13    4.15
   215.8     3.9  216.48    4.21  248.69    4.11  257.16    4.25  263.58    4.24
  290.52    3.86  306.63    3.78  307.97    3.79  311.75     4.4  312.76       4
  313.75    4.33  322.03    4.47  327.32    4.37  328.15    3.57  329.61    4.31
  332.82    4.12  343.14    4.13  352.26    4.38  357.33    4.41  361.12    4.63
  397.78    4.84  456.28    5.85
#Mann= 3 , 0 , 0
  156.11     .14       0  327.32    .067       0  329.61     .14       0
Bank Sta=327.32,329.61
XS Rating Curve= 0 ,0
Exp/Cntr=0.3,0.1

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
Type RM Length L Ch R = 1 ,5.1     ,32.75,32.75,32.75
XS GIS Cut Line= 4
         465519.         214041.         465517.         214042.
         465510.         214045.         465141.         214229.
#Sta/Elev= 30
  146.13    4.13  171.86    3.99  195.11    3.45  203.86    3.46  227.69       3
  230.08     2.7  268.57    2.88  293.17     2.5  311.51    2.66  322.06     2.5
  325.32    2.77  326.46     2.4  328.57    2.73  335.95     2.9  342.83    2.35
  344.15    2.75  356.45    2.19  368.93    2.25  375.71    1.98  381.22    2.29
   393.9    2.51  416.43    2.28  420.88    2.54  433.93    2.14  459.43    2.22
  469.67    1.63   503.7    2.66  540.97    2.49  553.41    3.03  567.07    3.19
#Mann= 3 , 0 , 0
  146.13     .14       0  368.93    .067       0  381.22     .14       0
Levee=0,,,-1,420.88,2.54,,
Bank Sta=368.93,381.22
XS Rating Curve= 0 ,0
Exp/Cntr=0.3,0.1

Type RM Length L Ch R = 2 ,4.15    ,,,
Bridge Culvert--1,0,-1,-1, 0
Deck Dist Width WeirC Skew NumUp NumDn MinLoCord MaxHiCord MaxSubmerge Is_Ogee
12,12.6,1.4,0, 74, 59, , , 0.98, 0, 0,0,,
  143.75  179.12  184.29  186.69  189.06  191.46  202.23  211.18  220.23  232.15
  242.74  251.55     260  272.17  290.76   291.8  295.09  297.42   297.8  299.01
  301.94  302.58   318.6  326.17  329.31  341.46  358.77     366  367.49  368.97
   370.2  372.39  396.83  409.82  410.97  417.77  463.91  472.56  475.08  477.92
  481.96  484.76  487.59  488.99  492.67  494.02  496.99  499.39  502.14  503.06
  504.96  506.13  507.39  523.85  524.99  526.08  529.38  530.74  531.97  534.32
  535.77  536.96  538.08   540.6  541.03  541.91     544  545.98  548.16  549.92
  552.15  556.07  557.97  565.56
    4.34    3.66     3.6    3.57    3.55    3.53    3.39     3.3    3.19    3.11
    3.02    2.98    2.87    2.86    2.74    2.67    2.67    2.66    2.69    2.68
    2.67    2.67    2.65    2.66     2.7     2.6    2.59     2.5     2.5    2.49
    2.49    2.54    2.55    2.51    2.45    2.42    2.43    2.48     2.5    2.53
    2.56    2.58    2.59     2.6    2.61    2.61    2.63    2.65    2.66    2.67
    2.68    2.65    2.65    2.75    2.79    2.82    2.86    2.91    2.92    2.94
    2.95    2.96    2.96    2.98    2.99    3.01    3.03    3.06    3.08    3.09
    3.11    3.13    3.24    3.21
                                                                                
                                                                                
                                                                                
                                                                                
                                                                                
                                                                                
                                                                                
                                
  123.41  129.91  137.83   139.4  140.72  142.18  152.81  156.95  157.32  158.15
  160.79   163.4  165.13  166.13  192.41  193.32  194.03  194.64  195.22  195.76
  196.19  198.95  201.95   203.1  205.32  206.49  208.09  213.43  225.11  227.13
  247.53  248.55  250.12  251.12  252.78  253.75  260.49  261.38  283.58  297.43
  304.56  340.61  370.77  389.98  423.22  437.85  455.65  458.71  459.34  461.41
  464.26  466.54  469.41   470.1  512.19  536.16  550.88  560.34  567.97
    4.28    4.07    3.89    3.88    3.86    3.85    3.68    3.65    3.69    3.68
    3.72    3.66    3.64    3.63    3.61     3.6     3.6    3.64    3.63    3.63
    3.63    3.62     3.6    3.58    3.56    3.53    3.51     3.4    3.35    3.33
    3.19    3.16    3.15    3.12     3.1    3.08    3.06    3.05    2.94    2.85
    2.82    2.79    2.77    2.76    2.67    2.65    2.64    2.65    2.65    2.67
    2.68    2.67    2.69    2.69    2.95    3.16    3.17    3.25    3.45
                                                                                
                                                                                
                                                                                
                                                                                
                                                                                
                                                                        
BR Coef=-1 , 0 , 0 ,, 0 ,,,0.8,-1,,0,
WSPro=,,,, 1 ,,,, 0 ,,,, 0 ,,,,-1 ,-1 ,-1 , 0 , 0 , 0 , 0 , 0
Culvert=1,1,,12.6,0.0166,0.5,1,1,1,1.05,375.71,1.01,364.34,Culvert #1  , 0 ,12
Culvert Bottom n=0.0166
BR U #Sta/Elev= 169
  146.13    4.13  146.14    4.13  148.15    4.03  149.91    4.01  150.74    3.98
  151.57    3.95  152.97    4.06  153.79    4.03  153.81    4.03  162.85    3.97
  167.33       4  168.76    4.01  171.86    3.99  174.93    3.83  176.56    3.77
  189.51    3.68  195.11    3.45  203.86    3.46  209.66    3.35  213.15    3.21
     215     3.2   218.6    3.15  223.71    3.05  223.77    3.05  223.89    3.05
  227.08    3.01  227.69       3  229.66    2.76  230.08     2.7  230.59    2.71
  230.85    2.71   231.8    2.71  238.93    2.77  241.52    2.84  253.04    2.86
  262.57    2.86  263.33    2.86  265.29    2.84  268.57    2.88  270.68    2.84
  273.97    2.79  275.57    2.76  277.18    2.74  282.24    2.64  293.17     2.5
  294.21    2.56  295.98    2.56  297.51    2.57  297.69    2.56   298.7    2.55
  307.47    2.63  310.49    2.65  311.51    2.66  312.05    2.64  322.06     2.5
  325.16    2.76  325.32    2.77   326.4    2.41  326.43     2.4  326.46     2.4
  326.48    2.41  326.69    2.44  328.57    2.73  328.77    2.74  331.63    2.79
     333    2.83   333.8    2.83  335.95     2.9  336.03    2.83   338.1    2.78
  339.58     2.7  340.56    2.67  342.45    2.41  342.83    2.35  343.07    2.44
  344.06    2.75  344.15    2.75   344.7    2.74  346.74    2.68  353.74    2.31
  356.45    2.19  358.33    2.19  366.66    2.21   367.4    2.22  368.93    2.25
  375.71    1.05  376.27    1.05  381.22    2.29  386.33    2.39  391.51     2.5
  392.05    2.48   393.9    2.51  398.85     2.5  399.52    2.48  399.74    2.49
  400.87    2.46  406.28    2.27  407.48    2.26   409.1    2.25  411.73    2.31
  412.27     2.3  415.45     2.3  416.43    2.28  417.84    2.35  419.19    2.42
  419.85    2.46  420.26    2.49  420.53    2.51  420.73    2.53  420.88    2.54
  429.58    2.23  430.27    2.24  433.93    2.14  434.58    2.15  435.13    2.16
  438.78    2.17  439.27    2.18  439.88    2.18  440.38    2.17  458.45    2.23
  458.63    2.22  459.43    2.22  461.96    2.03  466.29    1.73   467.9    1.71
  469.67    1.63  479.83    1.85  480.24    1.86  499.45    2.39  499.59     2.4
  500.08    2.44   503.7    2.66  504.35    2.66  505.19    2.67  505.89    2.66
  506.38    2.65  507.13    2.66  512.21    2.64  512.96    2.63  513.11    2.62
  513.47    2.62  513.59    2.61  514.77    2.59  514.92     2.6  518.66    2.56
  521.44    2.49  521.54    2.49  522.04    2.49  522.43    2.49  523.96    2.48
  524.01    2.43  524.32    2.47  524.49    2.47  540.31    2.49  540.63     2.5
  540.97    2.49  541.16     2.5  541.37    2.51  541.73    2.52  553.41    3.03
  561.49    3.18  562.42     3.2  563.99    3.23  564.55    3.24  565.26    3.26
  565.38    3.27  565.91    3.25  566.24    3.23  567.07    3.19
BR U #Mann= 3
  146.13      .2  368.93      .2  381.22      .2
BC Design=,, 0 ,, 0 ,,,,,,
BC Use User HTab Curves=0
BC User HTab FreeFlow(D)= 0

Type RM Length L Ch R = 1 ,4.1     ,27.91,27.91,27.91
XS GIS Cut Line= 5
         465508.         214011.         465503.         214013.
         465493.         214018.         465486.         214021.
         465117.         214205.
#Sta/Elev= 30
  130.54    3.41  155.71    2.84  167.03    2.95  171.41     3.2  198.25    2.93
  217.97    2.36  251.92    2.28  257.34    2.51  293.61     2.1  326.32    1.99
  327.97    1.81  355.21    1.19  358.52    1.19  359.19    1.39  364.69       1
  366.33    1.44  378.19    1.76  402.11    1.67   416.2    1.47   417.6     .97
  418.79    1.39  424.99    1.61  450.95     1.5  475.51     1.9  506.22    1.55
  520.64    2.19  529.86    2.25  544.15    2.75  560.06    2.84  566.77    2.66
#Mann= 3 , 0 , 0
  130.54     .14       0  359.19    .067       0  366.33     .14       0
Bank Sta=359.19,366.33
XS Rating Curve= 0 ,0
Exp/Cntr=0.3,0.1

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
Type RM Length L Ch R = 1 ,3.1     ,112,111.4,103.5
XS GIS Cut Line= 3
         465529.         213952.         465522.         213950.
         465091.         214169.
#Sta/Elev= 30
   95.17    3.05  115.17    2.25  128.06    2.06  136.33    2.27  145.14    1.92
  164.67     1.8  168.59    1.99   182.8    2.12  183.79    2.03  184.28    1.62
  185.09    2.02  200.25    2.38  215.54    2.32  238.12    1.92  259.15    1.82
  274.03    2.01  275.96    1.88  348.82    1.42  372.35     .63  394.21    1.48
  406.86    1.55  423.72    1.27  426.87    1.18  428.06     .63   429.8    1.21
  456.17    1.09  476.74    1.74  522.41    1.93  540.02    1.74  586.63    1.94
#Mann= 3 , 0 , 0
   95.17     .14       0  348.82    .067       0  394.21     .14       0
Bank Sta=348.82,394.21
XS Rating Curve= 0 ,0
Exp/Cntr=0.3,0.1

Chan Stop Cuts=-1
Use User Specified Reach Order=0
Composite Channel Slope=5

--- Lucky_global_v2.g02 (geometry) ---

Geom Title=K_fort
Program Version=4.10

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
River Reach=lucky           ,lucky

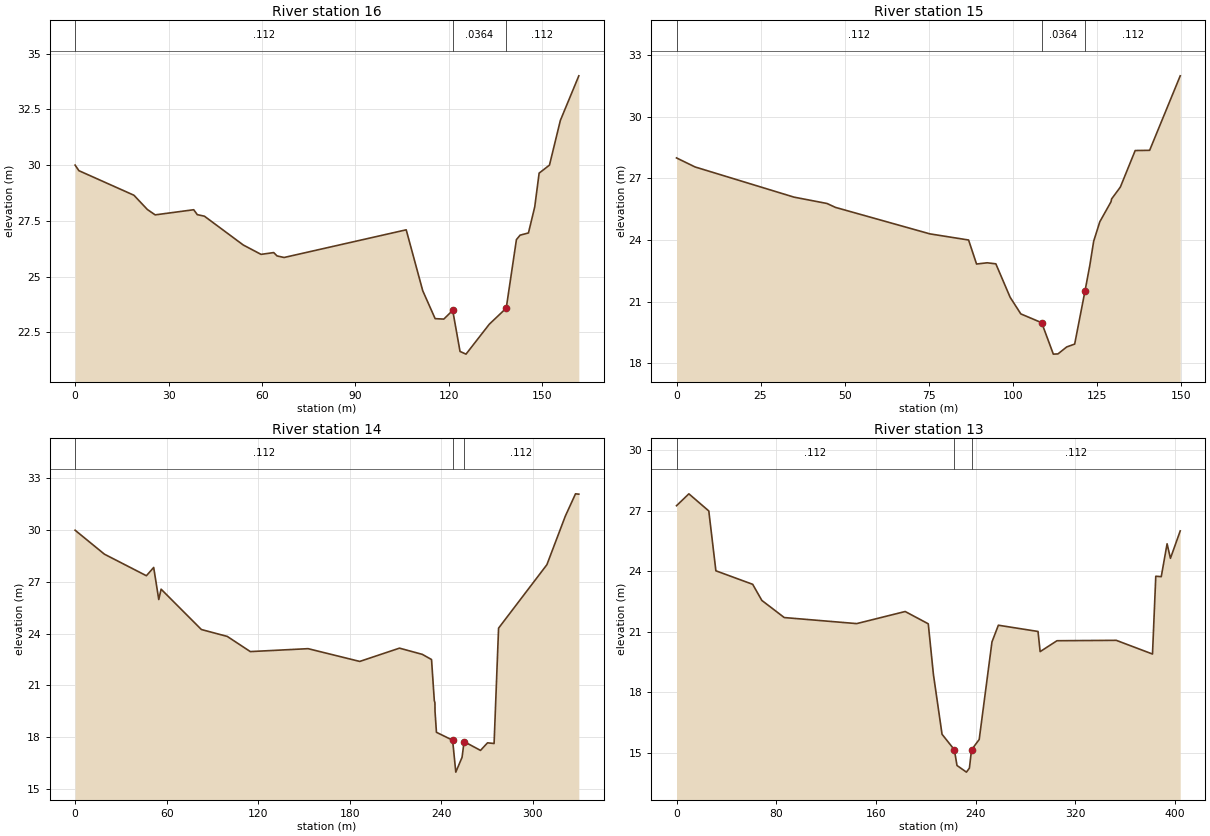
Type RM Length L Ch R = 1 ,16      ,137.04,117.31,101.36
XS GIS Cut Line= 6
466403.226999998214964.163000001466297.833999999214950.436000001
466286.513999999      214946.261      466283.695214945.800000001
466260.809500001      214937.737466245.226300001     214933.4109
#Sta/Elev= 30
       0      30    1.22   29.75   18.88   28.65    23.2   28.01    25.7   27.77
   38.08      28   39.22   27.78   41.52   27.71   53.98   26.42   59.69      26
   63.75   26.08   64.83   25.93   67.08   25.86  106.28    27.1  111.59   24.37
  115.57   23.12  118.35    23.1  121.21   23.49  123.56   21.65  125.48   21.53
  132.95   22.87  138.39   23.59  141.66   26.66  142.84   26.86  145.52   26.96
  147.54   28.13  148.95   29.64  152.27      30  155.76      32  161.69      34
#Mann= 3 , 0 , 0
       0    .112       0  121.21   .0364       0  138.39    .112       0
Bank Sta=121.21,138.39
XS Rating Curve= 0 ,0
Exp/Cntr=0.3,0.1

Type RM Length L Ch R = 1 ,15      ,153.31,142.94,123.08
XS GIS Cut Line= 6
466401.800999999      214801.932466315.445100002     214824.5331
466303.164999999      214829.272466300.153999999214830.187999999
466271.267399997214841.083000001466259.509499997214847.511499999
#Sta/Elev= 27
       0      28    5.52   27.56   34.94   26.09   44.77   25.78   47.28   25.59
   75.36    24.3   86.89      24   89.26   22.83    92.4   22.89      95   22.84
   99.25   21.21  102.43    20.4  108.64   19.97   112.1   18.44  113.47   18.45
  116.08   18.79  118.45   18.93  121.55   21.54  122.95   22.76   124.1   23.94
  125.93   24.89  129.25   25.86  129.43      26  132.04   26.58  136.45   28.36
  140.75   28.37  149.85      32
#Mann= 3 , 0 , 0
       0    .112       0  108.64   .0364       0  121.55    .112       0
Bank Sta=108.64,121.55
XS Rating Curve= 0 ,0
Exp/Cntr=0.3,0.1

Type RM Length L Ch R = 1 ,14      ,56.92,130.05,169.97
XS GIS Cut Line= 6
466418.269000001      214610.944466215.697999999214706.334000001
466194.939000003214738.586999999466189.443999998      214747.457
466185.178999998214753.904999999466159.436999999214796.301000001
#Sta/Elev= 30
       0      30   19.21   28.61   46.71   27.36   51.49   27.84   54.82   25.98
   56.35   26.58   82.75   24.24    99.7   23.84  114.81   22.96  152.64   23.13
   186.5   22.39  212.52   23.16  227.49    22.8  233.54    22.5  235.36   20.11
  235.76      20  235.82    19.5  236.75   18.28  247.35   17.82  249.43   15.97
  253.54   16.83  254.87   17.74  265.62   17.23  270.22   17.67  274.52   17.63
  277.46   24.32  309.12      28  321.21   30.82  327.87   32.11  330.04   32.09
#Mann= 3 , 0 , 0
       0    .112       0  247.35   .0364       0  254.87    .112       0
Bank Sta=247.35,254.87
XS Rating Curve= 0 ,0
Exp/Cntr=0.3,0.1

Type RM Length L Ch R = 1 ,13      ,3.6,7.11,3.21
XS GIS Cut Line= 6
466385.748000003214582.027000001466199.175999999     214646.4493
466180.346000001       214643.73466164.611000001214626.549000001
466148.531999998214617.608999999466012.998999998      214671.683
#Sta/Elev= 30
       0   27.25    9.93   27.84   25.91   26.99    31.6   24.02   61.12   23.35
   68.48   22.55   86.48    21.7  144.58    21.4   183.5      22  202.01   21.39
  206.14   18.88  213.06   15.91  222.95   15.14  225.06   14.36  232.64   14.03
  235.03   14.23  236.73   15.14  242.88   15.65  253.12   20.49  258.26   21.32
  290.08   21.01  291.77   20.01  305.28   20.55  352.86   20.57  381.93   19.89
  384.57   23.75  388.96   23.73  393.63   25.36  396.33   24.64  404.18      26
#Mann= 3 , 0 , 0
       0    .112       0  222.95   .0364       0  236.73    .112       0
Bank Sta=222.95,236.73
XS Rating Curve= 0 ,0
Exp/Cntr=0.3,0.1