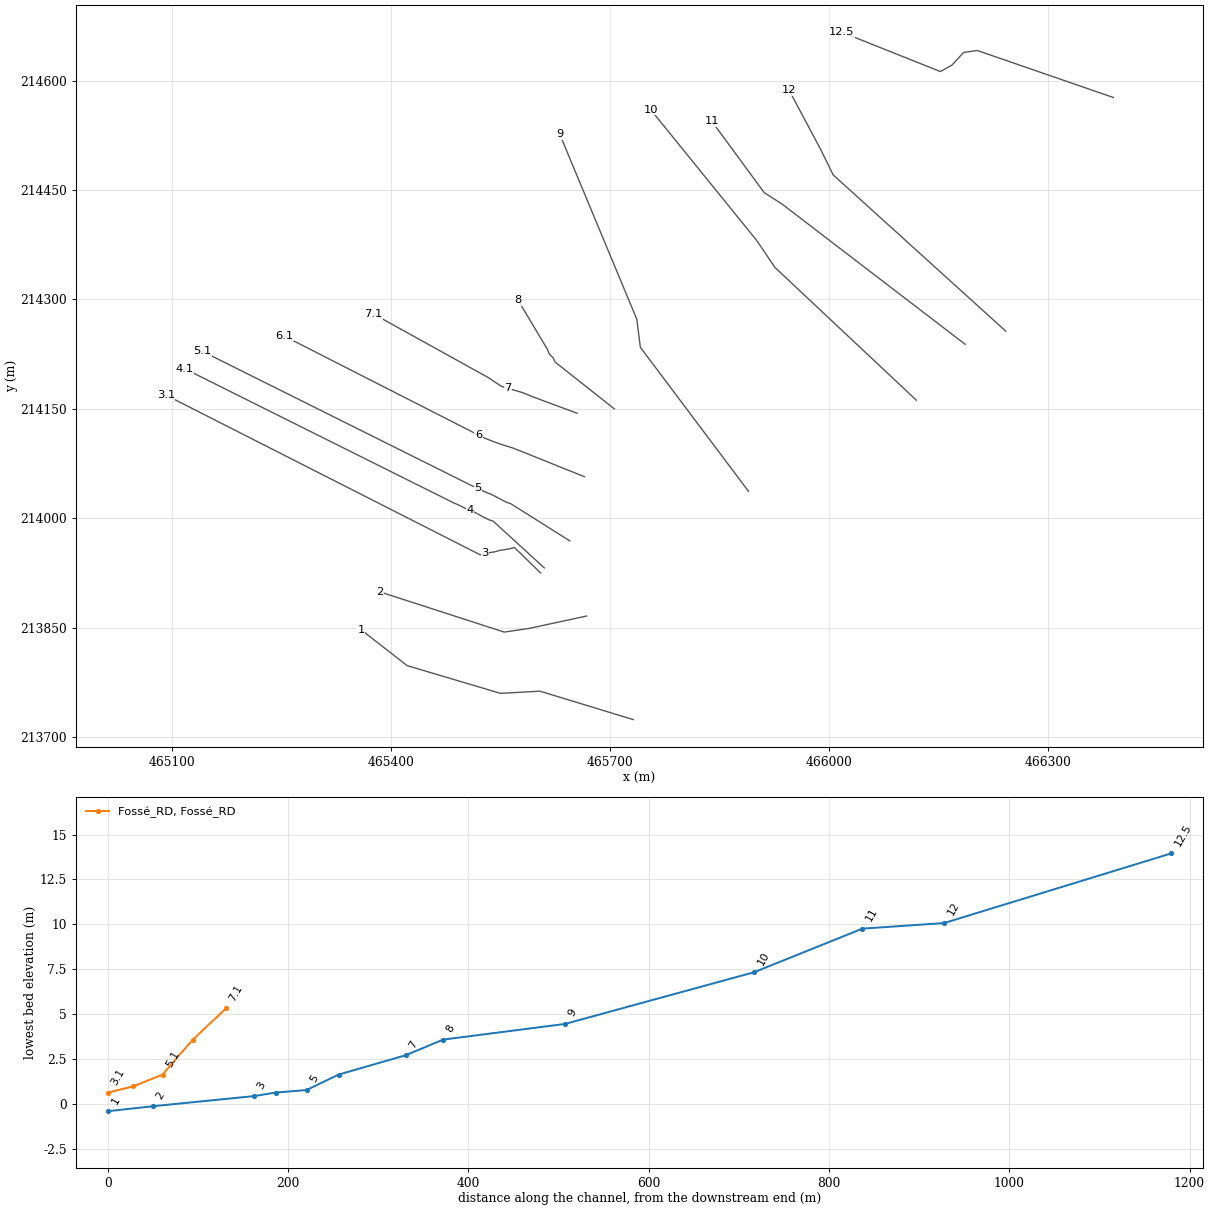
HEC-RAS study Lucky_global_v2.prj: Lucky_global_v2

--- Lucky_global_v2.g02 (geometry) --- (continued)

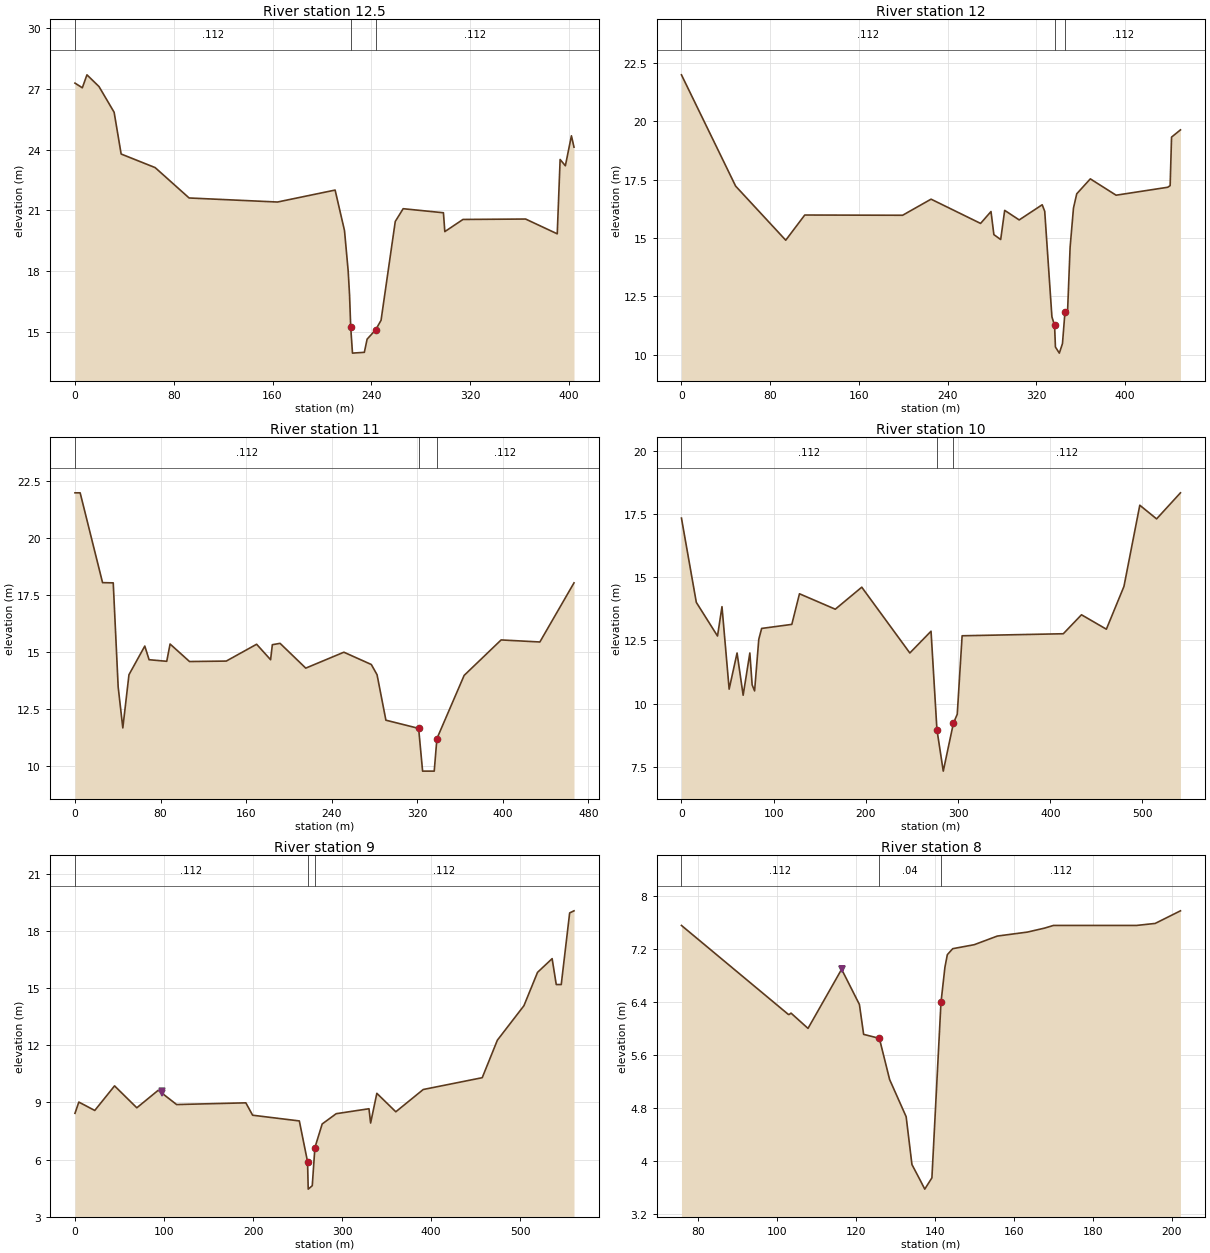
Type RM Length L Ch R = 1 ,12.5    ,277.13,252.07,155.83
XS GIS Cut Line= 6
466390.142800003     214576.8664466203.570799999214641.288699999
466184.740800001214638.569399999466169.005800001     214621.3884
466152.926799998     214612.4484466017.393799998214666.522399999
#Sta/Elev= 30
       0   27.28    5.96   27.05    9.69   27.69   19.46   27.11   31.71   25.84
   37.39   23.78   64.93   23.11   92.43   21.61  164.01   21.41  210.69      22
   218.3      20  221.28      18  222.38   16.83  223.34   15.22  224.76   13.95
  234.37   13.99  236.62   14.64  243.52    15.1   247.9   15.57  259.41   20.45
  265.81   21.08  298.42   20.88  299.56   19.95  314.27   20.55  364.99   20.57
  390.61   19.84  392.95   23.51  397.19    23.2   402.1   24.68  404.18   24.12
#Mann= 3 , 0 , 0
       0    .112       0  223.34   .0364       0  243.52    .112       0
Bank Sta=223.34,243.52
XS Rating Curve= 0 ,0
Exp/Cntr=0.3,0.1

Type RM Length L Ch R = 1 ,12      ,66.62,90.56,102.42
XS GIS Cut Line= 6
      466242.555      214256.569466006.034900002214470.762599999
465996.519000001      214490.137465995.189999998214492.643999999
465989.590000004214504.221000001465945.649099998214586.762700001
#Sta/Elev= 30
       0      22   48.84   17.23   94.02   14.91  111.16   15.99   199.4   15.98
  225.04   16.67  269.69   15.63  279.07   16.14  281.67   15.15  287.81   14.94
  291.41   16.19   304.5   15.78  325.23   16.43  327.51   16.15  333.99   11.63
  336.38   11.26  337.17   10.33  340.68   10.07  343.52   10.48  345.76   11.83
  348.14   11.89  350.39    14.6  353.44   16.29  356.38    16.9  368.62   17.54
  391.85   16.84   438.4   17.18  440.59   17.25  441.85   19.33  449.89   19.64
#Mann= 3 , 0 , 0
       0    .112       0  336.38   .0364       0  345.76    .112       0
Bank Sta=336.38,345.76
XS Rating Curve= 0 ,0
Exp/Cntr=0.3,0.1

Type RM Length L Ch R = 1 ,11      ,82.38,120.25,50.94
XS GIS Cut Line= 6
466186.972999997      214238.513465935.409299999214431.177200001
465922.670999996       214439.25     465920.2993     214440.7919
465911.469999999       214446.41465839.657099999214544.242799999
#Sta/Elev= 30
       0      22    4.82      22   25.78   18.05   35.76   18.04   40.38   13.46
   44.72   11.66   50.47      14   65.27   15.26   69.29   14.66    85.8   14.59
   88.91   15.35   107.1   14.58  141.45    14.6  169.83   15.34   182.9   14.66
  184.54   15.32  191.76   15.38  215.78   14.29  251.42   14.99  277.07   14.45
  282.45      14  290.73      12  321.33   11.64  325.03    9.76  335.91    9.76
  338.42   11.19  363.88   13.97  398.47   15.53  434.68   15.44   466.6   18.04
#Mann= 3 , 0 , 0
       0    .112       0  321.33   .0364       0  338.42    .112       0
Bank Sta=321.33,338.42
XS Rating Curve= 0 ,0
Exp/Cntr=0.3,0.1

Type RM Length L Ch R = 1 ,10      ,226.87,209.83,172.63
XS GIS Cut Line= 6
466120.006999999      214161.899465926.175999999214343.893999999
      465924.195214346.825200001465923.170100003     214348.3419
465901.305699997     214380.6943465755.920999996      214560.091
#Sta/Elev= 30
       0   17.33   16.12      14   39.11   12.67   43.96   13.83   51.72   10.57
   60.31      12   66.91   10.33   74.17      12   76.66   10.74   79.32    10.5
   83.87   12.54   86.97   12.97  119.69   13.13     128   14.34  166.85   13.73
  195.56    14.6   247.7      12  270.69   12.86  277.08    8.97  283.95    7.33
  294.93    9.22  299.12    9.58   304.4   12.68  414.16   12.76  433.86   13.51
  460.85   12.94  479.92   14.63  497.11   17.84  515.33    17.3  541.21   18.33
#Mann= 3 , 0 , 0
       0    .112       0  277.08     .04       0  294.93    .112       0
Bank Sta=277.08,294.93
XS Rating Curve= 0 ,0
Exp/Cntr=0.3,0.1

Type RM Length L Ch R = 1 ,9       ,80,135,150
XS GIS Cut Line= 6
465889.954000004214036.925000001465741.682999998214234.424000001
465739.877700001     214248.5703465739.745899998214249.603800001
465736.767999999214272.938999999      465631.158      214526.554
#Sta/Elev= 30
       0    8.43     4.3    9.02   22.22    8.58   44.45    9.87   69.46    8.72
   93.52    9.64  114.16    8.89  191.91    8.98  199.53    8.33  251.99    8.03
  261.22    5.89  261.97    4.45  266.51    4.63  269.48    6.63  277.65    7.87
  293.41    8.41  330.23    8.67  332.07    7.92  339.06    9.48  360.36    8.51
  391.16    9.68  457.43    10.3  474.45   12.27  504.28   14.08  519.56   15.83
  535.94   16.55  540.58   15.19  546.18   15.19  555.63   18.95  560.51   19.06
#Mann= 3 , 0 , 0
       0    .112       0  261.22     .04       0  269.48    .112       0
Levee=-1,98.06,9.59,0,,,,
Bank Sta=261.22,269.48
XS Rating Curve= 0 ,0
Exp/Cntr=0.3,0.1

Type RM Length L Ch R = 1 ,8       ,33.67,41.445,44.025
XS GIS Cut Line= 6
         465706.         214150.         465625.         214214.
         465622.         214220.         465617.         214225.
         465614.         214232.         465574.         214299.
#Sta/Elev= 29
   75.75    7.55  102.86    6.21  103.06    6.21   103.1    6.21  103.53    6.23
  107.84       6  116.36    6.89  120.87    6.36  121.94    5.91  125.93    5.85
  128.53    5.23  132.72    4.67  134.19    3.95  136.23    3.72  137.44    3.58
  139.25    3.75  141.55    6.39  142.55    6.92  143.16    7.11  144.53     7.2
  149.98    7.26  155.83    7.39  163.47    7.45  167.83    7.51  170.07    7.55
  191.15    7.55  194.26    7.57  195.85    7.58  202.27    7.77
#Mann= 3 , 0 , 0
   75.75    .112       0  125.93     .04       0  141.55    .112       0
Levee=-1,116.36,6.89,0,,,,
Bank Sta=125.93,141.55
XS Rating Curve= 0 ,0
Exp/Cntr=0.3,0.1

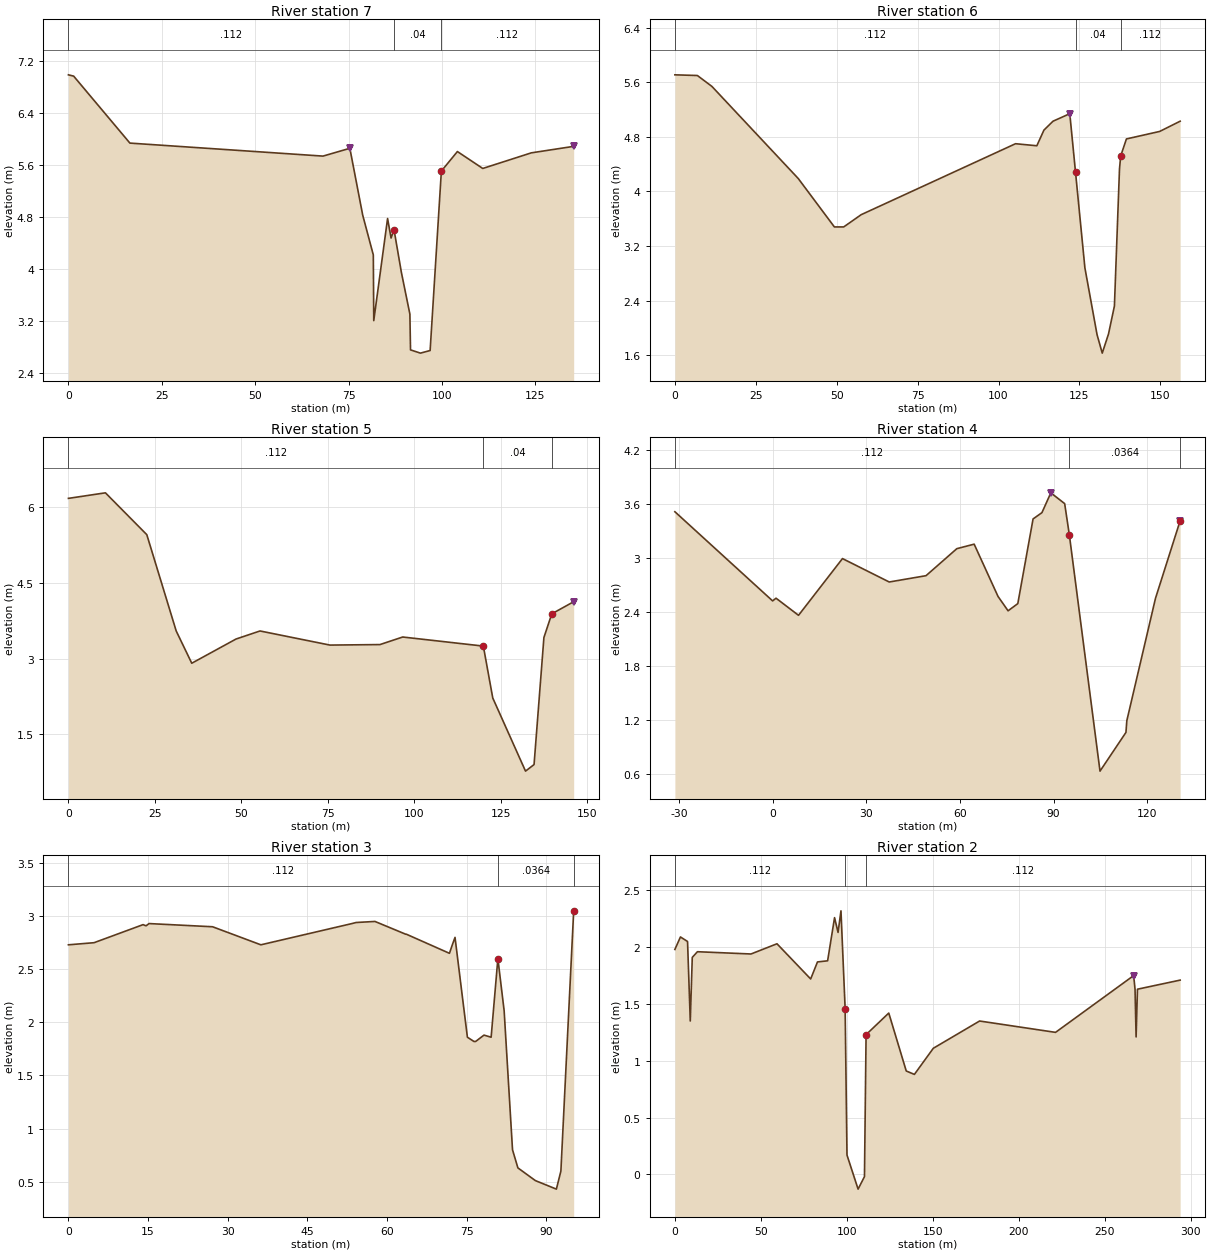
Type RM Length L Ch R = 1 ,7       ,75.66,74.62,74.2
XS GIS Cut Line= 5
         465655.         214144.         465593.         214167.
         465581.         214172.         465571.         214175.
         465560.         214178.
#Sta/Elev= 21
       0    6.99     1.4    6.97   16.46    5.94   68.15    5.74   75.34    5.86
   78.79    4.83   81.62    4.22   81.74    3.21   85.44    4.78   86.37    4.48
   87.16    4.61   89.14    3.95   91.41    3.31   91.58    2.76   94.23    2.71
   96.83    2.75   99.84    5.51  104.13    5.81  110.92    5.55  123.92    5.79
  135.26    5.89
#Mann= 3 , 0 , 0
       0    .112       0   87.16     .04       0   99.84    .112       0
Levee=-1,75.34,5.86,-1,135.26,5.89,,
Bank Sta=87.16,99.84
XS Rating Curve= 0 ,0
Exp/Cntr=0.3,0.1

Type RM Length L Ch R = 1 ,6       ,38.52,35.49,33.425
XS GIS Cut Line= 6
         465665.         214057.         465568.         214096.
         465552.         214101.         465538.         214106.
         465528.         214110.         465520.         214114.
#Sta/Elev= 23
       0    5.71    6.94     5.7   11.44    5.54   38.11    4.19   49.28    3.48
   52.16    3.48   57.57    3.66  105.25     4.7  111.83    4.67  114.03     4.9
  116.83    5.03  122.01    5.14  123.79   4.279  126.68    2.88  130.44     1.9
  132.04    1.63  133.97    1.91   135.8    2.32  137.37    4.33  137.74    4.52
  139.51    4.77  149.78    4.88  156.11    5.03
#Mann= 3 , 0 , 0
       0    .112       0  123.79     .04       0  137.74    .112       0
Levee=-1,122.01,5.14,0,,,,
Bank Sta=123.79,137.74
XS Rating Curve= 0 ,0
Exp/Cntr=0.3,0.1

Type RM Length L Ch R = 1 ,5       ,42.01,34.34,32.75
XS GIS Cut Line= 6
         465645.         213969.         465564.         214020.
         465558.         214022.         465539.         214032.
         465527.         214037.         465519.         214041.
#Sta/Elev= 17
       0    6.18    10.7    6.29   22.67    5.46   31.17    3.55   35.67    2.91
   48.47    3.39   55.41    3.55   75.64    3.27    90.1    3.28   96.68    3.43
     120    3.25  122.73    2.22   132.2     .77  134.67      .9  137.52    3.42
   139.8    3.89  146.13    4.13
#Mann= 3 , 0 , 0
       0    .112       0     120     .04       0   139.8    .112       0
Levee=0,,,-1,146.13,4.13,,
Bank Sta=120,139.8
XS Rating Curve= 0 ,0
Exp/Cntr=0.3,0.1

Type RM Length L Ch R = 1 ,4       ,11.42,24.37,27.91
XS GIS Cut Line= 6
         465610.         213932.         465540.         213996.
         465534.         213998.         465526.         214002.
         465515.         214008.         465508.         214011.
#Sta/Elev= 22
   -31.3    3.51       0    2.52     1.1    2.55     8.3    2.36   22.38    2.99
   37.35    2.73   49.14     2.8   59.01     3.1   64.56    3.15    72.2    2.57
   75.42    2.41   78.54    2.49   83.43    3.43   86.27     3.5   89.12    3.72
   93.55     3.6   95.06    3.25  104.87     .63  113.18    1.06  113.46    1.19
  122.65    2.55  130.54    3.41
#Mann= 3 , 0 , 0
   -31.3    .112       0   95.06   .0364       0  130.54    .112       0
Levee=-1,89.12,3.72,-1,130.54,3.41,,
Bank Sta=95.06,130.54
XS Rating Curve= 0 ,0
Exp/Cntr=0.3,0.1

Type RM Length L Ch R = 1 ,3       ,112,111.4,103.5
XS GIS Cut Line= 6
         465605.         213925.         465569.         213960.
         465562.         213958.         465549.         213956.
         465542.         213954.         465529.         213952.
#Sta/Elev= 30
       0    2.73    4.83    2.75   14.06    2.92   14.55    2.91   14.66    2.91
   15.18    2.93   27.15     2.9   36.25    2.73    53.4    2.93   54.19    2.94
   57.74    2.95   63.52    2.83   63.65    2.83   71.77    2.65   72.31    2.73
   72.82     2.8   75.15    1.86   76.39    1.82    76.7    1.82   78.28    1.88
   79.62    1.86   80.89     2.6   82.07    2.11   83.65      .8   84.66     .63
   87.96     .51   87.97     .51   91.91     .43   92.76      .6   95.17    3.05
#Mann= 3 , 0 , 0
       0    .112       0   80.89   .0364       0   95.17    .112       0
Bank Sta=80.89,95.17
XS Rating Curve= 0 ,0
Exp/Cntr=0.3,0.1

Type RM Length L Ch R = 1 ,2       ,44,50.3,42.6
XS GIS Cut Line= 4
         465668.         213866.         465589.         213849.
         465555.         213844.         465385.         213899.
#Sta/Elev= 30
       0    1.98    3.23    2.09    7.36    2.05    8.95    1.35   10.11    1.91
   13.11    1.96   44.28    1.94    59.4    2.03      79    1.72   82.96    1.87
   88.86    1.88    92.9    2.26   94.93    2.13   96.63    2.32   99.05    1.46
  100.13     .17  106.59    -.13   110.3    -.02  111.24    1.23  124.44    1.42
  134.61     .91  139.35     .88  150.36    1.11  177.29    1.35  221.47    1.25
  266.93    1.75  267.72    1.63  268.34    1.21  269.13    1.63  293.97    1.71
#Mann= 3 , 0 , 0
       0    .112       0   99.05   .0364       0  111.24    .112       0
Levee=0,,,-1,266.93,1.75,,
Bank Sta=99.05,111.24
XS Rating Curve= 0 ,0
Exp/Cntr=0.3,0.1

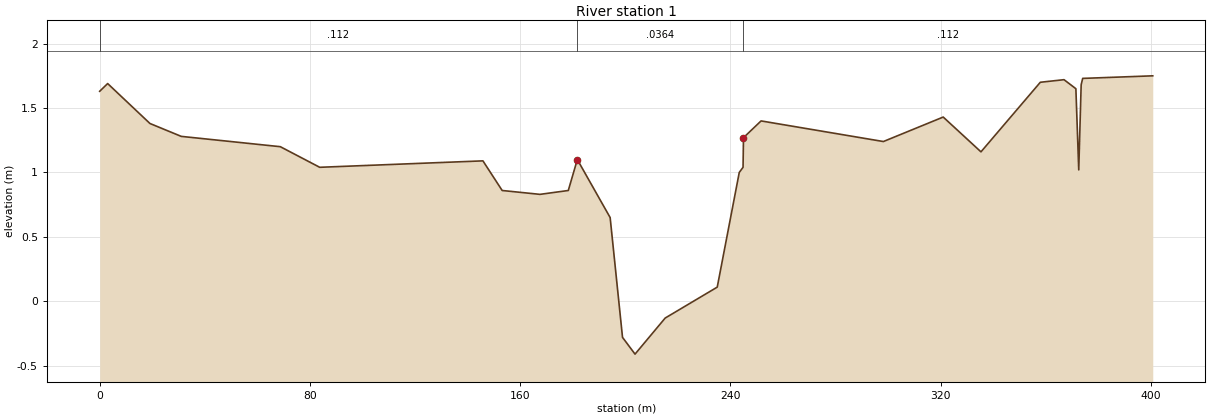
Type RM Length L Ch R = 1 ,1       ,,,
XS GIS Cut Line= 5
         465732.         213724.         465604.         213763.
         465550.         213760.         465422.         213798.
         465359.         213847.
#Sta/Elev= 30
       0    1.63    3.03    1.69   19.13    1.38   31.04    1.28   68.74     1.2
   83.74    1.04  145.85    1.09  153.18     .86  167.57     .83  178.34     .86
  181.78     1.1  194.27     .65  198.98    -.28  203.74    -.41  215.22    -.13
  235.03     .11  243.41       1  244.85    1.04  245.02    1.27  251.71     1.4
  298.26    1.24  321.03    1.43   335.4    1.16  357.99     1.7  367.01    1.72
  371.52    1.65  372.61    1.02  373.53    1.68  374.11    1.73  400.78    1.75
#Mann= 3 , 0 , 0
       0    .112       0  181.78   .0364       0  245.02    .112       0
Bank Sta=181.78,245.02
XS Rating Curve= 0 ,0
Exp/Cntr=0.3,0.1

River Reach=Fossé_RD        ,Fossé_RD

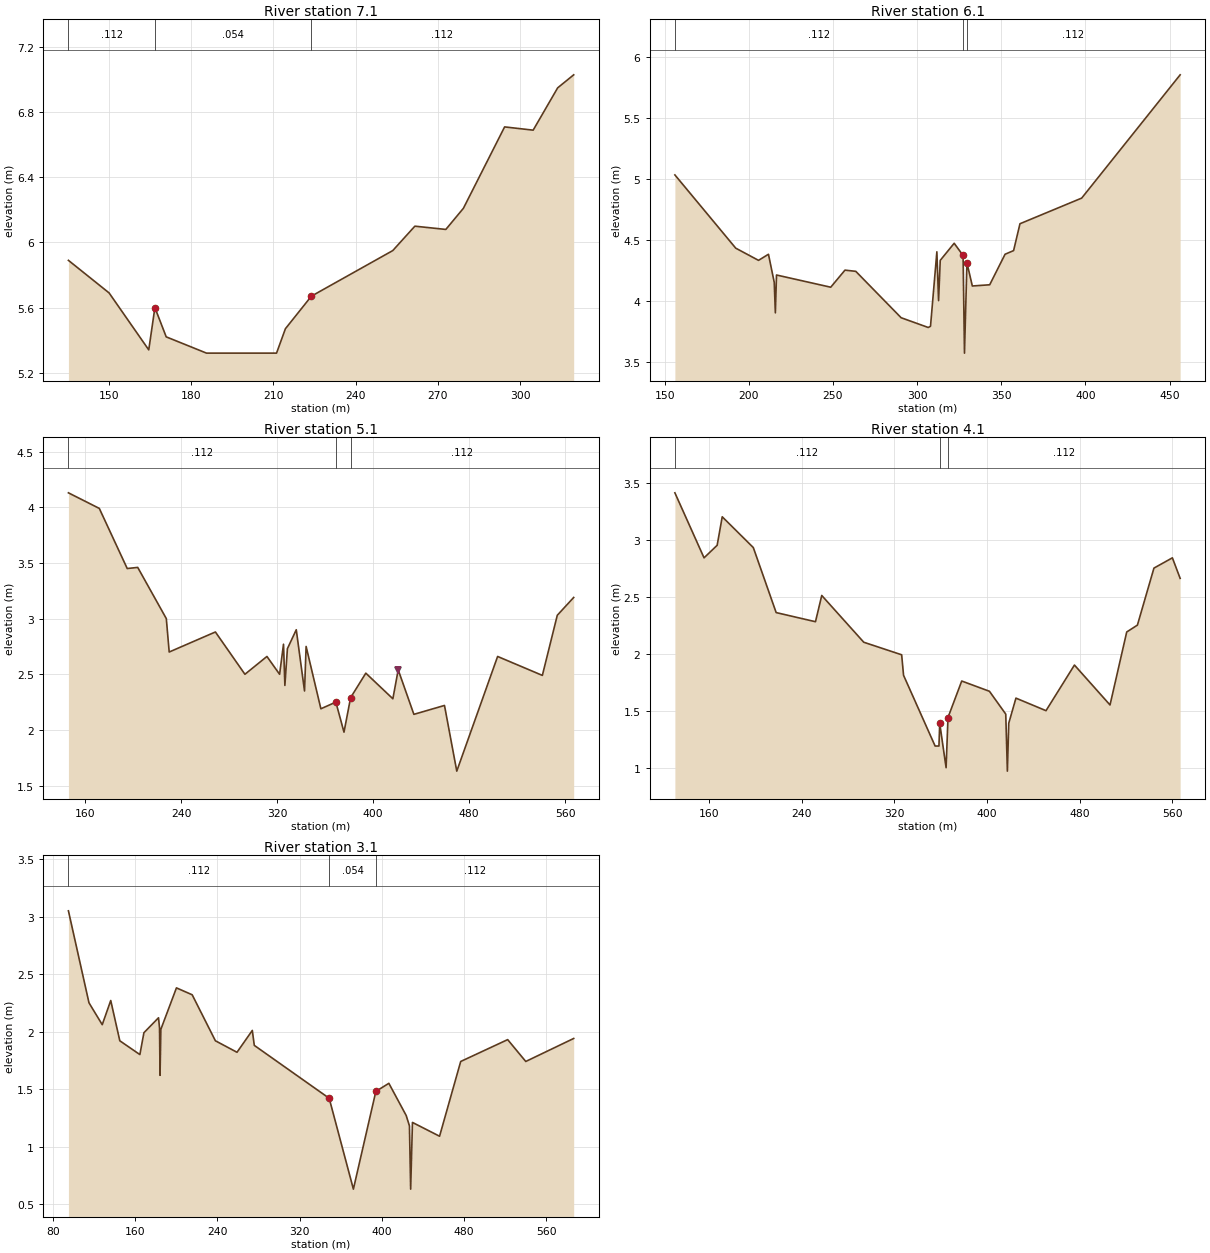
Type RM Length L Ch R = 1 ,7.1     ,37.105,37.105,37.105
XS GIS Cut Line= 4
         465560.         214178.         465551.         214181.
         465533.         214193.         465376.         214280.
#Sta/Elev= 17
  135.26    5.89  150.09    5.69  164.56    5.34   166.8     5.6  170.92    5.42
  185.62    5.32  211.17    5.32  214.41    5.47  223.88    5.67  253.56    5.95
  261.62     6.1  272.92    6.08  279.33    6.21  294.36    6.71  304.77    6.69
  313.71    6.95  319.55    7.03
#Mann= 3 , 0 , 0
  135.26    .112       0   166.8    .054       0  223.88    .112       0
Bank Sta=166.8,223.88
XS Rating Curve= 0 ,0
Exp/Cntr=0.3,0.1

Type RM Length L Ch R = 1 ,6.1     ,33.425,33.425,33.425
XS GIS Cut Line= 2
         465520.         214114.         465253.         214250.
#Sta/Elev= 27
  156.11    5.03  192.25    4.43  205.79    4.33   211.7    4.38  215.13    4.15
   215.8     3.9  216.48    4.21  248.69    4.11  257.16    4.25  263.58    4.24
  290.52    3.86  306.63    3.78  307.97    3.79  311.75     4.4  312.76       4
  313.75    4.33  322.03    4.47  327.32    4.37  328.15    3.57  329.61    4.31
  332.82    4.12  343.14    4.13  352.26    4.38  357.33    4.41  361.12    4.63
  397.78    4.84  456.28    5.85
#Mann= 3 , 0 , 0
  156.11    .112       0  327.32    .054       0  329.61    .112       0
Bank Sta=327.32,329.61
XS Rating Curve= 0 ,0
Exp/Cntr=0.3,0.1

Type RM Length L Ch R = 1 ,5.1     ,32.75,32.75,32.75
XS GIS Cut Line= 4
         465519.         214041.         465517.         214042.
         465510.         214045.         465141.         214229.
#Sta/Elev= 30
  146.13    4.13  171.86    3.99  195.11    3.45  203.86    3.46  227.69       3
  230.08     2.7  268.57    2.88  293.17     2.5  311.51    2.66  322.06     2.5
  325.32    2.77  326.46     2.4  328.57    2.73  335.95     2.9  342.83    2.35
  344.15    2.75  356.45    2.19  368.93    2.25  375.71    1.98  381.22    2.29
   393.9    2.51  416.43    2.28  420.88    2.54  433.93    2.14  459.43    2.22
  469.67    1.63   503.7    2.66  540.97    2.49  553.41    3.03  567.07    3.19
#Mann= 3 , 0 , 0
  146.13    .112       0  368.93    .054       0  381.22    .112       0
Levee=0,,,-1,420.88,2.54,,
Bank Sta=368.93,381.22
XS Rating Curve= 0 ,0
Exp/Cntr=0.3,0.1

Type RM Length L Ch R = 1 ,4.1     ,27.91,27.91,27.91
XS GIS Cut Line= 5
         465508.         214011.         465503.         214013.
         465493.         214018.         465486.         214021.
         465117.         214205.
#Sta/Elev= 30
  130.54    3.41  155.71    2.84  167.03    2.95  171.41     3.2  198.25    2.93
  217.97    2.36  251.92    2.28  257.34    2.51  293.61     2.1  326.32    1.99
  327.97    1.81  355.21    1.19  358.52    1.19  359.19    1.39  364.69       1
  366.33    1.44  378.19    1.76  402.11    1.67   416.2    1.47   417.6     .97
  418.79    1.39  424.99    1.61  450.95     1.5  475.51     1.9  506.22    1.55
  520.64    2.19  529.86    2.25  544.15    2.75  560.06    2.84  566.77    2.66
#Mann= 3 , 0 , 0
  130.54    .112       0  359.19    .054       0  366.33    .112       0
Bank Sta=359.19,366.33
XS Rating Curve= 0 ,0
Exp/Cntr=0.3,0.1

Type RM Length L Ch R = 1 ,3.1     ,112,111.4,103.5
XS GIS Cut Line= 3
         465529.         213952.         465522.         213950.
         465091.         214169.
#Sta/Elev= 30
   95.17    3.05  115.17    2.25  128.06    2.06  136.33    2.27  145.14    1.92
  164.67     1.8  168.59    1.99   182.8    2.12  183.79    2.03  184.28    1.62
  185.09    2.02  200.25    2.38  215.54    2.32  238.12    1.92  259.15    1.82
  274.03    2.01  275.96    1.88  348.82    1.42  372.35     .63  394.21    1.48
  406.86    1.55  423.72    1.27  426.87    1.18  428.06     .63   429.8    1.21
  456.17    1.09  476.74    1.74  522.41    1.93  540.02    1.74  586.63    1.94
#Mann= 3 , 0 , 0
   95.17    .112       0  348.82    .054       0  394.21    .112       0
Bank Sta=348.82,394.21
XS Rating Curve= 0 ,0
Exp/Cntr=0.3,0.1

--- Lucky_global_v2.g03 (geometry) ---

Geom Title=K_faible
Program Version=4.10

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
River Reach=lucky           ,lucky

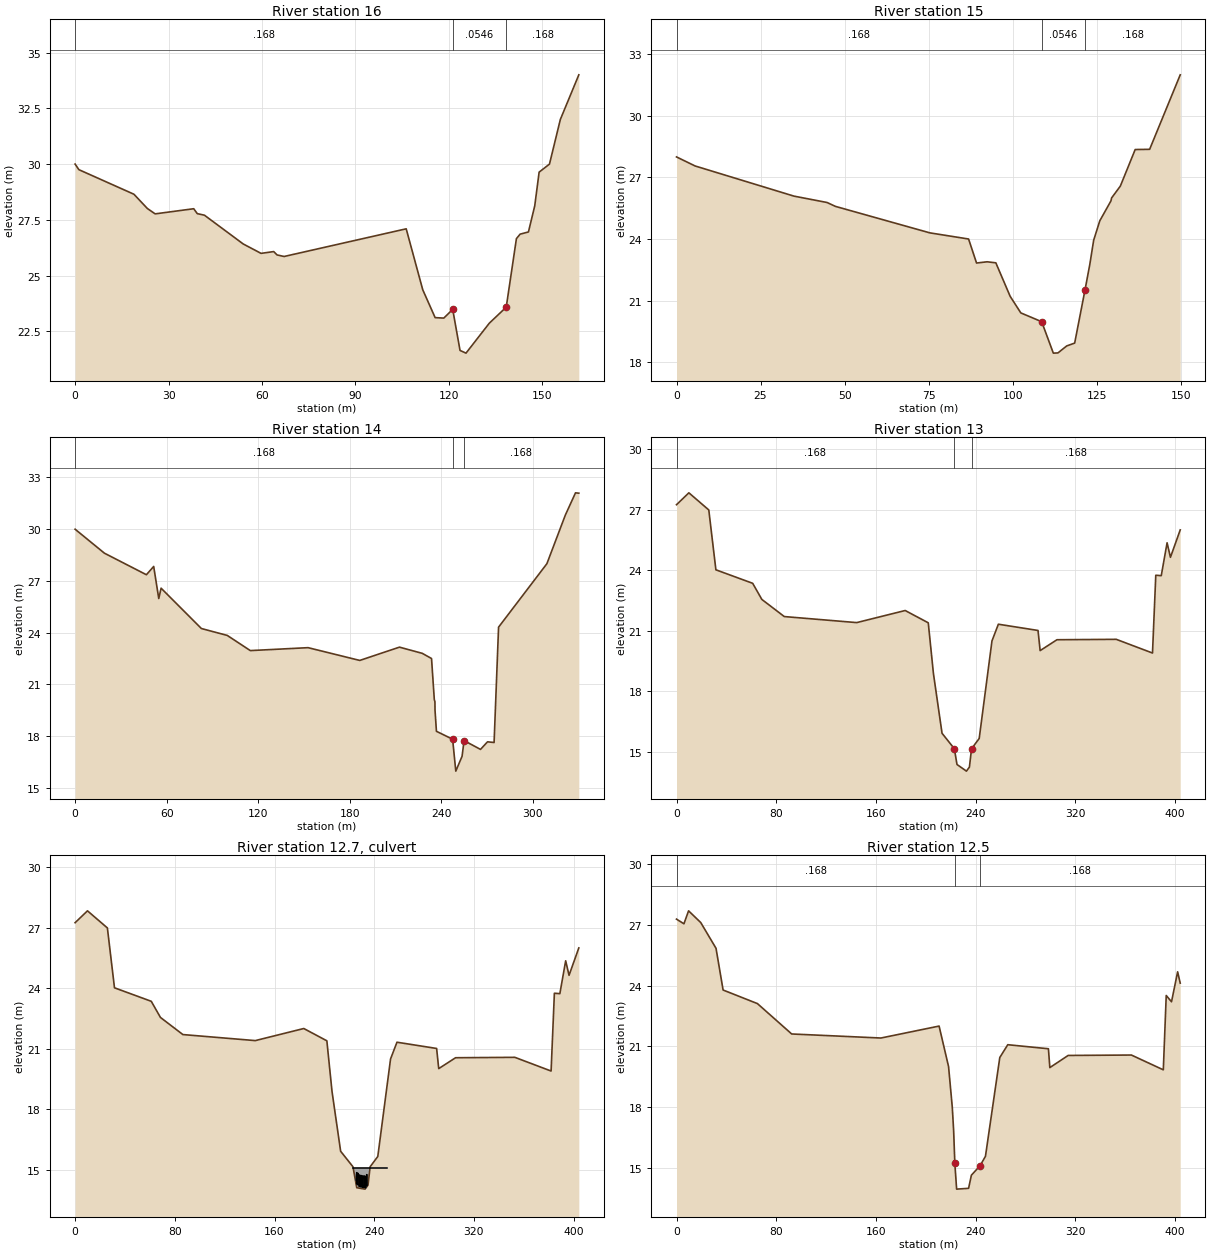
Type RM Length L Ch R = 1 ,16      ,137.04,117.31,101.36
XS GIS Cut Line= 6
466403.226999998214964.163000001466297.833999999214950.436000001
466286.513999999      214946.261      466283.695214945.800000001
466260.809500001      214937.737466245.226300001     214933.4109
#Sta/Elev= 30
       0      30    1.22   29.75   18.88   28.65    23.2   28.01    25.7   27.77
   38.08      28   39.22   27.78   41.52   27.71   53.98   26.42   59.69      26
   63.75   26.08   64.83   25.93   67.08   25.86  106.28    27.1  111.59   24.37
  115.57   23.12  118.35    23.1  121.21   23.49  123.56   21.65  125.48   21.53
  132.95   22.87  138.39   23.59  141.66   26.66  142.84   26.86  145.52   26.96
  147.54   28.13  148.95   29.64  152.27      30  155.76      32  161.69      34
#Mann= 3 , 0 , 0
       0    .168       0  121.21   .0546       0  138.39    .168       0
Bank Sta=121.21,138.39
XS Rating Curve= 0 ,0
Exp/Cntr=0.3,0.1

Type RM Length L Ch R = 1 ,15      ,153.31,142.94,123.08
XS GIS Cut Line= 6
466401.800999999      214801.932466315.445100002     214824.5331
466303.164999999      214829.272466300.153999999214830.187999999
466271.267399997214841.083000001466259.509499997214847.511499999
#Sta/Elev= 27
       0      28    5.52   27.56   34.94   26.09   44.77   25.78   47.28   25.59
   75.36    24.3   86.89      24   89.26   22.83    92.4   22.89      95   22.84
   99.25   21.21  102.43    20.4  108.64   19.97   112.1   18.44  113.47   18.45
  116.08   18.79  118.45   18.93  121.55   21.54  122.95   22.76   124.1   23.94
  125.93   24.89  129.25   25.86  129.43      26  132.04   26.58  136.45   28.36
  140.75   28.37  149.85      32
#Mann= 3 , 0 , 0
       0    .168       0  108.64   .0546       0  121.55    .168       0
Bank Sta=108.64,121.55
XS Rating Curve= 0 ,0
Exp/Cntr=0.3,0.1

Type RM Length L Ch R = 1 ,14      ,56.92,130.05,169.97
XS GIS Cut Line= 6
466418.269000001      214610.944466215.697999999214706.334000001
466194.939000003214738.586999999466189.443999998      214747.457
466185.178999998214753.904999999466159.436999999214796.301000001
#Sta/Elev= 30
       0      30   19.21   28.61   46.71   27.36   51.49   27.84   54.82   25.98
   56.35   26.58   82.75   24.24    99.7   23.84  114.81   22.96  152.64   23.13
   186.5   22.39  212.52   23.16  227.49    22.8  233.54    22.5  235.36   20.11
  235.76      20  235.82    19.5  236.75   18.28  247.35   17.82  249.43   15.97
  253.54   16.83  254.87   17.74  265.62   17.23  270.22   17.67  274.52   17.63
  277.46   24.32  309.12      28  321.21   30.82  327.87   32.11  330.04   32.09
#Mann= 3 , 0 , 0
       0    .168       0  247.35   .0546       0  254.87    .168       0
Bank Sta=247.35,254.87
XS Rating Curve= 0 ,0
Exp/Cntr=0.3,0.1

Type RM Length L Ch R = 1 ,13      ,3.6,7.11,3.21
XS GIS Cut Line= 6
466385.748000003214582.027000001466199.175999999     214646.4493
466180.346000001       214643.73466164.611000001214626.549000001
466148.531999998214617.608999999466012.998999998      214671.683
#Sta/Elev= 30
       0   27.25    9.93   27.84   25.91   26.99    31.6   24.02   61.12   23.35
   68.48   22.55   86.48    21.7  144.58    21.4   183.5      22  202.01   21.39
  206.14   18.88  213.06   15.91  222.95   15.14  225.06   14.36  232.64   14.03
  235.03   14.23  236.73   15.14  242.88   15.65  253.12   20.49  258.26   21.32
  290.08   21.01  291.77   20.01  305.28   20.55  352.86   20.57  381.93   19.89
  384.57   23.75  388.96   23.73  393.63   25.36  396.33   24.64  404.18      26
#Mann= 3 , 0 , 0
       0    .168       0  222.95   .0546       0  236.73    .168       0
Bank Sta=222.95,236.73
XS Rating Curve= 0 ,0
Exp/Cntr=0.3,0.1

Type RM Length L Ch R = 2 ,12.7    ,,,
Bridge Culvert--1,0,-1,-1, 0
Deck Dist Width WeirC Skew NumUp NumDn MinLoCord MaxHiCord MaxSubmerge Is_Ogee
2,2.2,1.4,0, 2, 2, , , 0.98, 0, 0,0,,
  222.95     250
    15.1    15.1
                
  222.95     250
    15.1    15.1
                
BR Coef=-1 , 0 , 0 ,, 0 ,,,0.8,-1,,0,
WSPro=,,,, 1 ,,,, 0 ,,,, 0 ,,,,-1 ,-1 ,-1 , 0 , 0 , 0 , 0 , 0
Culvert=1,0.6,,2.2,0.016,0.5,1,1,1,14.27,226,14.15,226,Culvert #1  , 0 ,2
Culvert Bottom n=0.016
Culvert=1,0.6,,2.2,0.016,0.5,1,1,1,14.23,227,14.25,227,Culvert #2  , 0 ,2
Culvert Bottom n=0.016
Culvert=1,0.6,,2.2,0.016,0.5,1,1,1,14.15,228,14.14,228,Culvert #3  , 0 ,2
Culvert Bottom n=0.016
Culvert=1,0.6,,2.2,0.016,0.5,1,1,1,14.13,229,14.12,229,Culvert #4  , 0 ,2
Culvert Bottom n=0.016
Culvert=1,0.6,,2.2,0.016,0.5,1,1,1,14.12,230,14.09,230,Culvert #5  , 0 ,2
Culvert Bottom n=0.016
Culvert=1,0.6,,2.2,0.016,0.5,1,1,1,14.1,231,14.13,231,Culvert #6  , 0 ,2
Culvert Bottom n=0.016
Culvert=1,0.6,,2.2,0.016,0.5,1,1,1,14.1,232,14.12,232,Culvert #7  , 0 ,2
Culvert Bottom n=0.016
Culvert=1,0.6,,2.2,0.016,0.5,1,1,1,14.08,233,14.12,233,Culvert #8  , 0 ,2
Culvert Bottom n=0.016
Culvert=1,0.6,,2.2,0.016,0.5,1,1,1,14.17,234,14.14,234,Culvert #9  , 0 ,2
Culvert Bottom n=0.016
BR U #Sta/Elev= 30
       0   27.25    9.93   27.84   25.91   26.99    31.6   24.02   61.12   23.35
   68.48   22.55   86.48    21.7  144.58    21.4   183.5      22  202.01   21.39
  206.14   18.88  213.06   15.91  222.95   15.14     226    14.1  232.64   14.03
  235.03   14.23  236.73   15.14  242.88   15.65  253.12   20.49  258.26   21.32
  290.08   21.01  291.77   20.01  305.28   20.55  352.86   20.57  381.93   19.89
  384.57   23.75  388.96   23.73  393.63   25.36  396.33   24.64  404.18      26
BR U #Mann= 3
       0    .168  222.95   .0546  236.73    .168
BR D #Sta/Elev= 30
       0   27.28    5.96   27.05    9.69   27.69   19.46   27.11   31.71   25.84
   37.39   23.78   64.93   23.11   92.43   21.61  164.01   21.41  210.69      22
   218.3      20  221.28      18  222.38   16.83  223.34   15.22  224.76   13.95
  234.37   13.99  236.62   14.64  243.52    15.1   247.9   15.57  255.41   19.04
  261.06   20.78  298.42   20.88  299.56   19.95  314.27   20.55  371.76   20.56
  390.61   19.84  392.95   23.51  397.19    23.2   402.1   24.68  404.18   24.12
BR D #Mann= 4
       0    .168  223.34   .0546  243.52    .168  261.06    .168
BR D Banks=,243.52
BC Design=,, 0 ,, 0 ,,,,,,
BC Use User HTab Curves=0
BC User HTab FreeFlow(D)= 0

Type RM Length L Ch R = 1 ,12.5    ,277.13,252.07,155.83
XS GIS Cut Line= 6
466390.142800003     214576.8664466203.570799999214641.288699999
466184.740800001214638.569399999466169.005800001     214621.3884
466152.926799998     214612.4484466017.393799998214666.522399999
#Sta/Elev= 30
       0   27.28    5.96   27.05    9.69   27.69   19.46   27.11   31.71   25.84
   37.39   23.78   64.93   23.11   92.43   21.61  164.01   21.41  210.69      22
   218.3      20  221.28      18  222.38   16.83  223.34   15.22  224.76   13.95
  234.37   13.99  236.62   14.64  243.52    15.1   247.9   15.57  259.41   20.45
  265.81   21.08  298.42   20.88  299.56   19.95  314.27   20.55  364.99   20.57
  390.61   19.84  392.95   23.51  397.19    23.2   402.1   24.68  404.18   24.12
#Mann= 3 , 0 , 0
       0    .168       0  223.34   .0546       0  243.52    .168       0
Bank Sta=223.34,243.52
XS Rating Curve= 0 ,0
Exp/Cntr=0.3,0.1

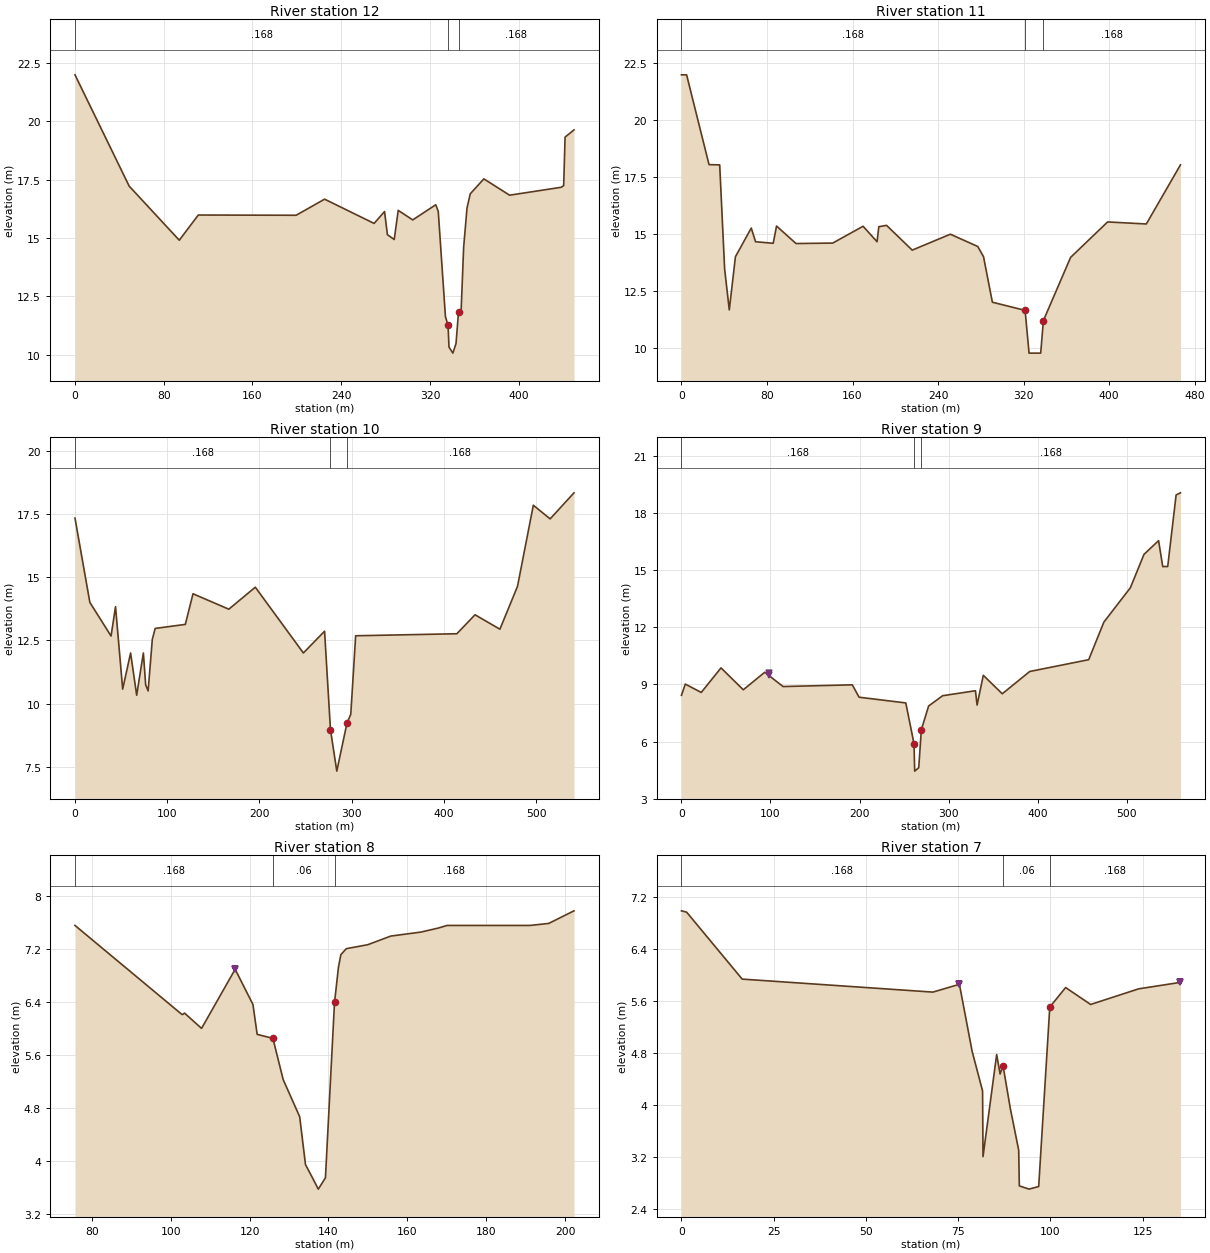
Type RM Length L Ch R = 1 ,12      ,66.62,90.56,102.42
XS GIS Cut Line= 6
      466242.555      214256.569466006.034900002214470.762599999
465996.519000001      214490.137465995.189999998214492.643999999
465989.590000004214504.221000001465945.649099998214586.762700001
#Sta/Elev= 30
       0      22   48.84   17.23   94.02   14.91  111.16   15.99   199.4   15.98
  225.04   16.67  269.69   15.63  279.07   16.14  281.67   15.15  287.81   14.94
  291.41   16.19   304.5   15.78  325.23   16.43  327.51   16.15  333.99   11.63
  336.38   11.26  337.17   10.33  340.68   10.07  343.52   10.48  345.76   11.83
  348.14   11.89  350.39    14.6  353.44   16.29  356.38    16.9  368.62   17.54
  391.85   16.84   438.4   17.18  440.59   17.25  441.85   19.33  449.89   19.64
#Mann= 3 , 0 , 0
       0    .168       0  336.38   .0546       0  345.76    .168       0
Bank Sta=336.38,345.76
XS Rating Curve= 0 ,0
Exp/Cntr=0.3,0.1

Type RM Length L Ch R = 1 ,11      ,82.38,120.25,50.94
XS GIS Cut Line= 6
466186.972999997      214238.513465935.409299999214431.177200001
465922.670999996       214439.25     465920.2993     214440.7919
465911.469999999       214446.41465839.657099999214544.242799999
#Sta/Elev= 30
       0      22    4.82      22   25.78   18.05   35.76   18.04   40.38   13.46
   44.72   11.66   50.47      14   65.27   15.26   69.29   14.66    85.8   14.59
   88.91   15.35   107.1   14.58  141.45    14.6  169.83   15.34   182.9   14.66
  184.54   15.32  191.76   15.38  215.78   14.29  251.42   14.99  277.07   14.45
  282.45      14  290.73      12  321.33   11.64  325.03    9.76  335.91    9.76
  338.42   11.19  363.88   13.97  398.47   15.53  434.68   15.44   466.6   18.04
#Mann= 3 , 0 , 0
       0    .168       0  321.33   .0546       0  338.42    .168       0
Bank Sta=321.33,338.42
XS Rating Curve= 0 ,0
Exp/Cntr=0.3,0.1

Type RM Length L Ch R = 1 ,10      ,226.87,209.83,172.63
XS GIS Cut Line= 6
466120.006999999      214161.899465926.175999999214343.893999999
      465924.195214346.825200001465923.170100003     214348.3419
465901.305699997     214380.6943465755.920999996      214560.091
#Sta/Elev= 30
       0   17.33   16.12      14   39.11   12.67   43.96   13.83   51.72   10.57
   60.31      12   66.91   10.33   74.17      12   76.66   10.74   79.32    10.5
   83.87   12.54   86.97   12.97  119.69   13.13     128   14.34  166.85   13.73
  195.56    14.6   247.7      12  270.69   12.86  277.08    8.97  283.95    7.33
  294.93    9.22  299.12    9.58   304.4   12.68  414.16   12.76  433.86   13.51
  460.85   12.94  479.92   14.63  497.11   17.84  515.33    17.3  541.21   18.33
#Mann= 3 , 0 , 0
       0    .168       0  277.08     .06       0  294.93    .168       0
Bank Sta=277.08,294.93
XS Rating Curve= 0 ,0
Exp/Cntr=0.3,0.1

Type RM Length L Ch R = 1 ,9       ,80,135,150
XS GIS Cut Line= 6
465889.954000004214036.925000001465741.682999998214234.424000001
465739.877700001     214248.5703465739.745899998214249.603800001
465736.767999999214272.938999999      465631.158      214526.554
#Sta/Elev= 30
       0    8.43     4.3    9.02   22.22    8.58   44.45    9.87   69.46    8.72
   93.52    9.64  114.16    8.89  191.91    8.98  199.53    8.33  251.99    8.03
  261.22    5.89  261.97    4.45  266.51    4.63  269.48    6.63  277.65    7.87
  293.41    8.41  330.23    8.67  332.07    7.92  339.06    9.48  360.36    8.51
  391.16    9.68  457.43    10.3  474.45   12.27  504.28   14.08  519.56   15.83
  535.94   16.55  540.58   15.19  546.18   15.19  555.63   18.95  560.51   19.06
#Mann= 3 , 0 , 0
       0    .168       0  261.22     .06       0  269.48    .168       0
Levee=-1,98.06,9.59,0,,,,
Bank Sta=261.22,269.48
XS Rating Curve= 0 ,0
Exp/Cntr=0.3,0.1

Type RM Length L Ch R = 1 ,8       ,33.67,41.445,44.025
XS GIS Cut Line= 6
         465706.         214150.         465625.         214214.
         465622.         214220.         465617.         214225.
         465614.         214232.         465574.         214299.
#Sta/Elev= 29
   75.75    7.55  102.86    6.21  103.06    6.21   103.1    6.21  103.53    6.23
  107.84       6  116.36    6.89  120.87    6.36  121.94    5.91  125.93    5.85
  128.53    5.23  132.72    4.67  134.19    3.95  136.23    3.72  137.44    3.58
  139.25    3.75  141.55    6.39  142.55    6.92  143.16    7.11  144.53     7.2
  149.98    7.26  155.83    7.39  163.47    7.45  167.83    7.51  170.07    7.55
  191.15    7.55  194.26    7.57  195.85    7.58  202.27    7.77
#Mann= 3 , 0 , 0
   75.75    .168       0  125.93     .06       0  141.55    .168       0
Levee=-1,116.36,6.89,0,,,,
Bank Sta=125.93,141.55
XS Rating Curve= 0 ,0
Exp/Cntr=0.3,0.1

Type RM Length L Ch R = 1 ,7       ,75.66,74.62,74.2
XS GIS Cut Line= 5
         465655.         214144.         465593.         214167.
         465581.         214172.         465571.         214175.
         465560.         214178.
#Sta/Elev= 21
       0    6.99     1.4    6.97   16.46    5.94   68.15    5.74   75.34    5.86
   78.79    4.83   81.62    4.22   81.74    3.21   85.44    4.78   86.37    4.48
   87.16    4.61   89.14    3.95   91.41    3.31   91.58    2.76   94.23    2.71
   96.83    2.75   99.84    5.51  104.13    5.81  110.92    5.55  123.92    5.79
  135.26    5.89
#Mann= 3 , 0 , 0
       0    .168       0   87.16     .06       0   99.84    .168       0
Levee=-1,75.34,5.86,-1,135.26,5.89,,
Bank Sta=87.16,99.84
XS Rating Curve= 0 ,0
Exp/Cntr=0.3,0.1

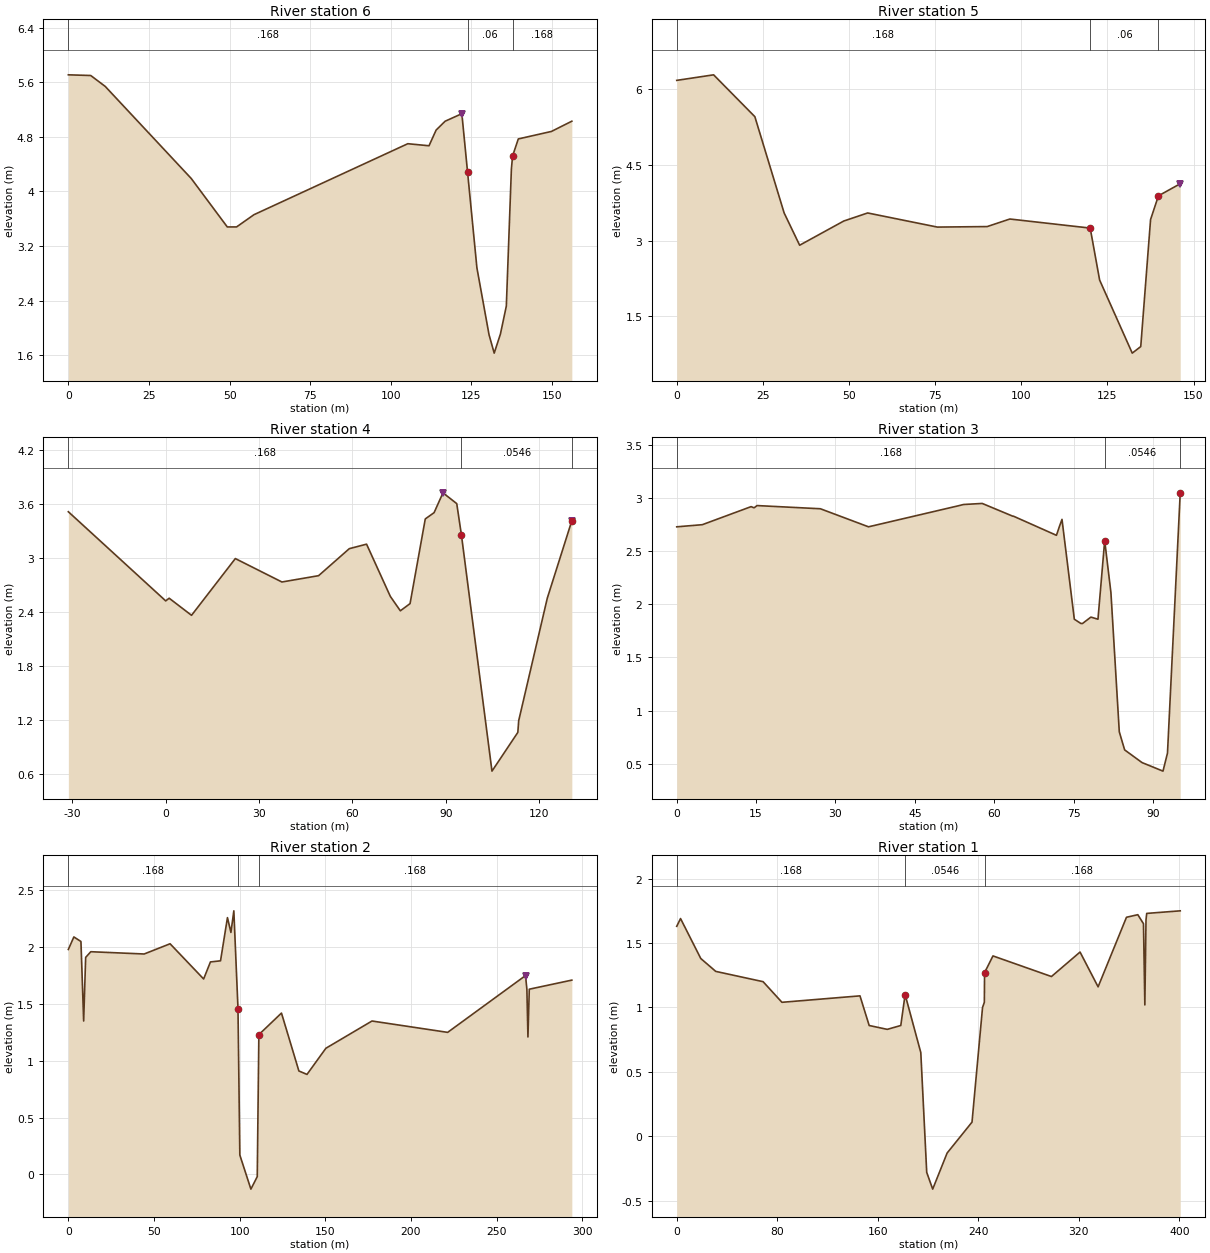
Type RM Length L Ch R = 1 ,6       ,38.52,35.49,33.425
XS GIS Cut Line= 6
         465665.         214057.         465568.         214096.
         465552.         214101.         465538.         214106.
         465528.         214110.         465520.         214114.
#Sta/Elev= 23
       0    5.71    6.94     5.7   11.44    5.54   38.11    4.19   49.28    3.48
   52.16    3.48   57.57    3.66  105.25     4.7  111.83    4.67  114.03     4.9
  116.83    5.03  122.01    5.14  123.79   4.279  126.68    2.88  130.44     1.9
  132.04    1.63  133.97    1.91   135.8    2.32  137.37    4.33  137.74    4.52
  139.51    4.77  149.78    4.88  156.11    5.03
#Mann= 3 , 0 , 0
       0    .168       0  123.79     .06       0  137.74    .168       0
Levee=-1,122.01,5.14,0,,,,
Bank Sta=123.79,137.74
XS Rating Curve= 0 ,0
Exp/Cntr=0.3,0.1

Type RM Length L Ch R = 1 ,5       ,42.01,34.34,32.75
XS GIS Cut Line= 6
         465645.         213969.         465564.         214020.
         465558.         214022.         465539.         214032.
         465527.         214037.         465519.         214041.
#Sta/Elev= 17
       0    6.18    10.7    6.29   22.67    5.46   31.17    3.55   35.67    2.91
   48.47    3.39   55.41    3.55   75.64    3.27    90.1    3.28   96.68    3.43
     120    3.25  122.73    2.22   132.2     .77  134.67      .9  137.52    3.42
   139.8    3.89  146.13    4.13
#Mann= 3 , 0 , 0
       0    .168       0     120     .06       0   139.8    .168       0
Levee=0,,,-1,146.13,4.13,,
Bank Sta=120,139.8
XS Rating Curve= 0 ,0
Exp/Cntr=0.3,0.1

Type RM Length L Ch R = 1 ,4       ,11.42,24.37,27.91
XS GIS Cut Line= 6
         465610.         213932.         465540.         213996.
         465534.         213998.         465526.         214002.
         465515.         214008.         465508.         214011.
#Sta/Elev= 22
   -31.3    3.51       0    2.52     1.1    2.55     8.3    2.36   22.38    2.99
   37.35    2.73   49.14     2.8   59.01     3.1   64.56    3.15    72.2    2.57
   75.42    2.41   78.54    2.49   83.43    3.43   86.27     3.5   89.12    3.72
   93.55     3.6   95.06    3.25  104.87     .63  113.18    1.06  113.46    1.19
  122.65    2.55  130.54    3.41
#Mann= 3 , 0 , 0
   -31.3    .168       0   95.06   .0546       0  130.54    .168       0
Levee=-1,89.12,3.72,-1,130.54,3.41,,
Bank Sta=95.06,130.54
XS Rating Curve= 0 ,0
Exp/Cntr=0.3,0.1

Type RM Length L Ch R = 1 ,3       ,112,111.4,103.5
XS GIS Cut Line= 6
         465605.         213925.         465569.         213960.
         465562.         213958.         465549.         213956.
         465542.         213954.         465529.         213952.
#Sta/Elev= 30
       0    2.73    4.83    2.75   14.06    2.92   14.55    2.91   14.66    2.91
   15.18    2.93   27.15     2.9   36.25    2.73    53.4    2.93   54.19    2.94
   57.74    2.95   63.52    2.83   63.65    2.83   71.77    2.65   72.31    2.73
   72.82     2.8   75.15    1.86   76.39    1.82    76.7    1.82   78.28    1.88
   79.62    1.86   80.89     2.6   82.07    2.11   83.65      .8   84.66     .63
   87.96     .51   87.97     .51   91.91     .43   92.76      .6   95.17    3.05
#Mann= 3 , 0 , 0
       0    .168       0   80.89   .0546       0   95.17    .168       0
Bank Sta=80.89,95.17
XS Rating Curve= 0 ,0
Exp/Cntr=0.3,0.1

Type RM Length L Ch R = 1 ,2       ,44,50.3,42.6
XS GIS Cut Line= 4
         465668.         213866.         465589.         213849.
         465555.         213844.         465385.         213899.
#Sta/Elev= 30
       0    1.98    3.23    2.09    7.36    2.05    8.95    1.35   10.11    1.91
   13.11    1.96   44.28    1.94    59.4    2.03      79    1.72   82.96    1.87
   88.86    1.88    92.9    2.26   94.93    2.13   96.63    2.32   99.05    1.46
  100.13     .17  106.59    -.13   110.3    -.02  111.24    1.23  124.44    1.42
  134.61     .91  139.35     .88  150.36    1.11  177.29    1.35  221.47    1.25
  266.93    1.75  267.72    1.63  268.34    1.21  269.13    1.63  293.97    1.71
#Mann= 3 , 0 , 0
       0    .168       0   99.05   .0546       0  111.24    .168       0
Levee=0,,,-1,266.93,1.75,,
Bank Sta=99.05,111.24
XS Rating Curve= 0 ,0
Exp/Cntr=0.3,0.1

Type RM Length L Ch R = 1 ,1       ,,,
XS GIS Cut Line= 5
         465732.         213724.         465604.         213763.
         465550.         213760.         465422.         213798.
         465359.         213847.
#Sta/Elev= 30
       0    1.63    3.03    1.69   19.13    1.38   31.04    1.28   68.74     1.2
   83.74    1.04  145.85    1.09  153.18     .86  167.57     .83  178.34     .86
  181.78     1.1  194.27     .65  198.98    -.28  203.74    -.41  215.22    -.13
  235.03     .11  243.41       1  244.85    1.04  245.02    1.27  251.71     1.4
  298.26    1.24  321.03    1.43   335.4    1.16  357.99     1.7  367.01    1.72
  371.52    1.65  372.61    1.02  373.53    1.68  374.11    1.73  400.78    1.75
#Mann= 3 , 0 , 0
       0    .168       0  181.78   .0546       0  245.02    .168       0
Bank Sta=181.78,245.02
XS Rating Curve= 0 ,0
Exp/Cntr=0.3,0.1

River Reach=Fossé_RD        ,Fossé_RD