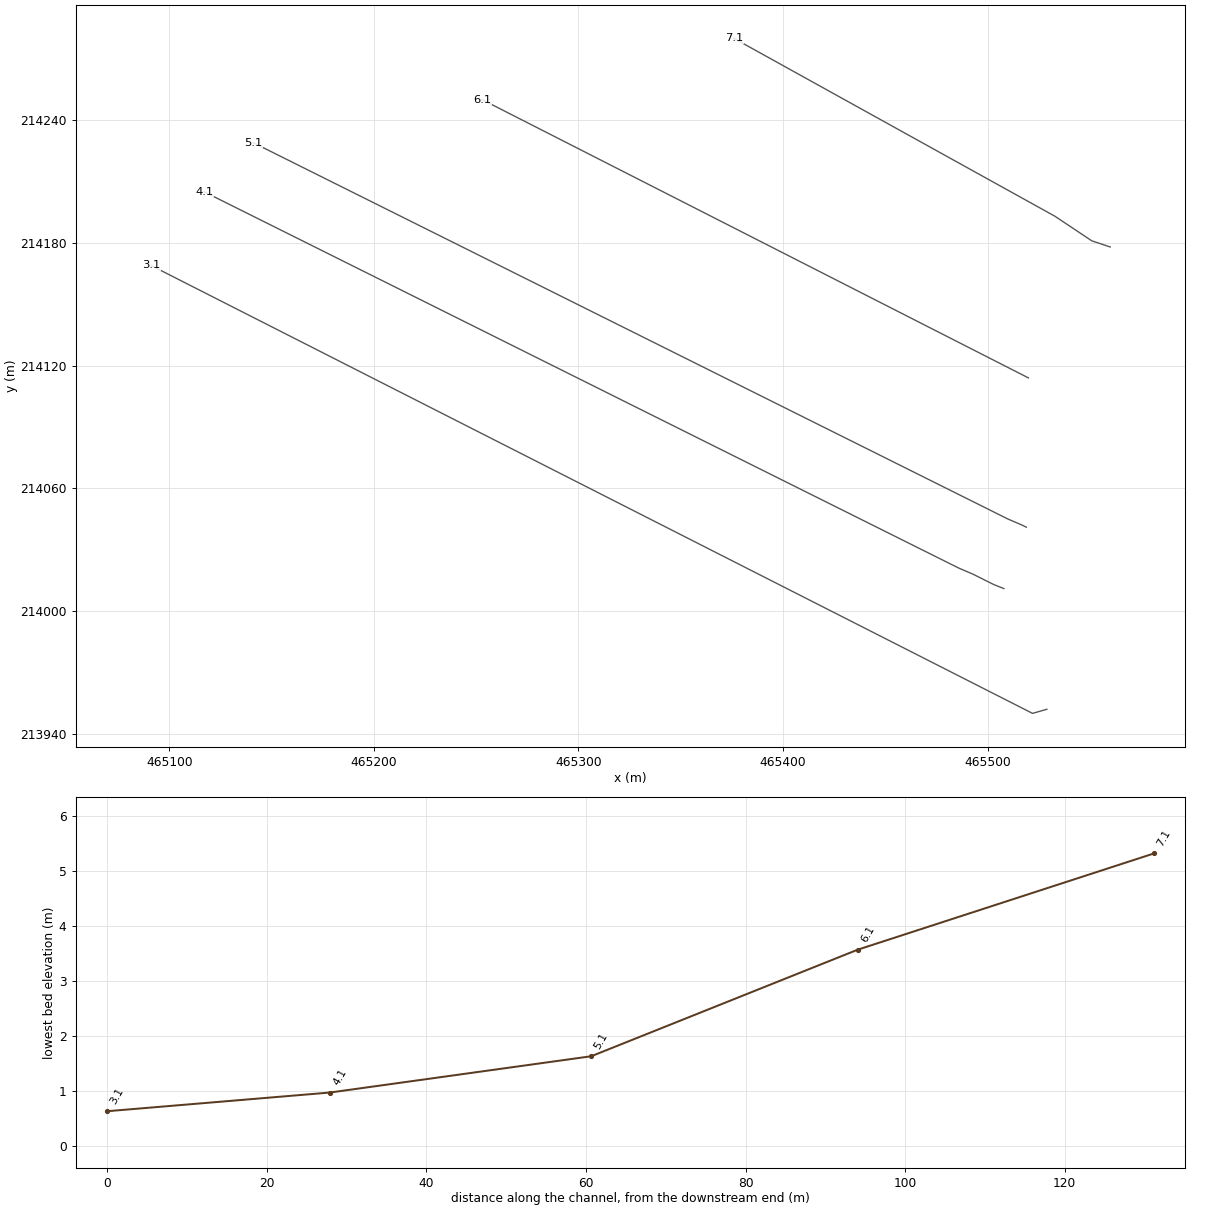
HEC-RAS study Lucky_global_v2.prj: Lucky_global_v2

--- Lucky_global_v2.g03 (geometry) --- (continued)

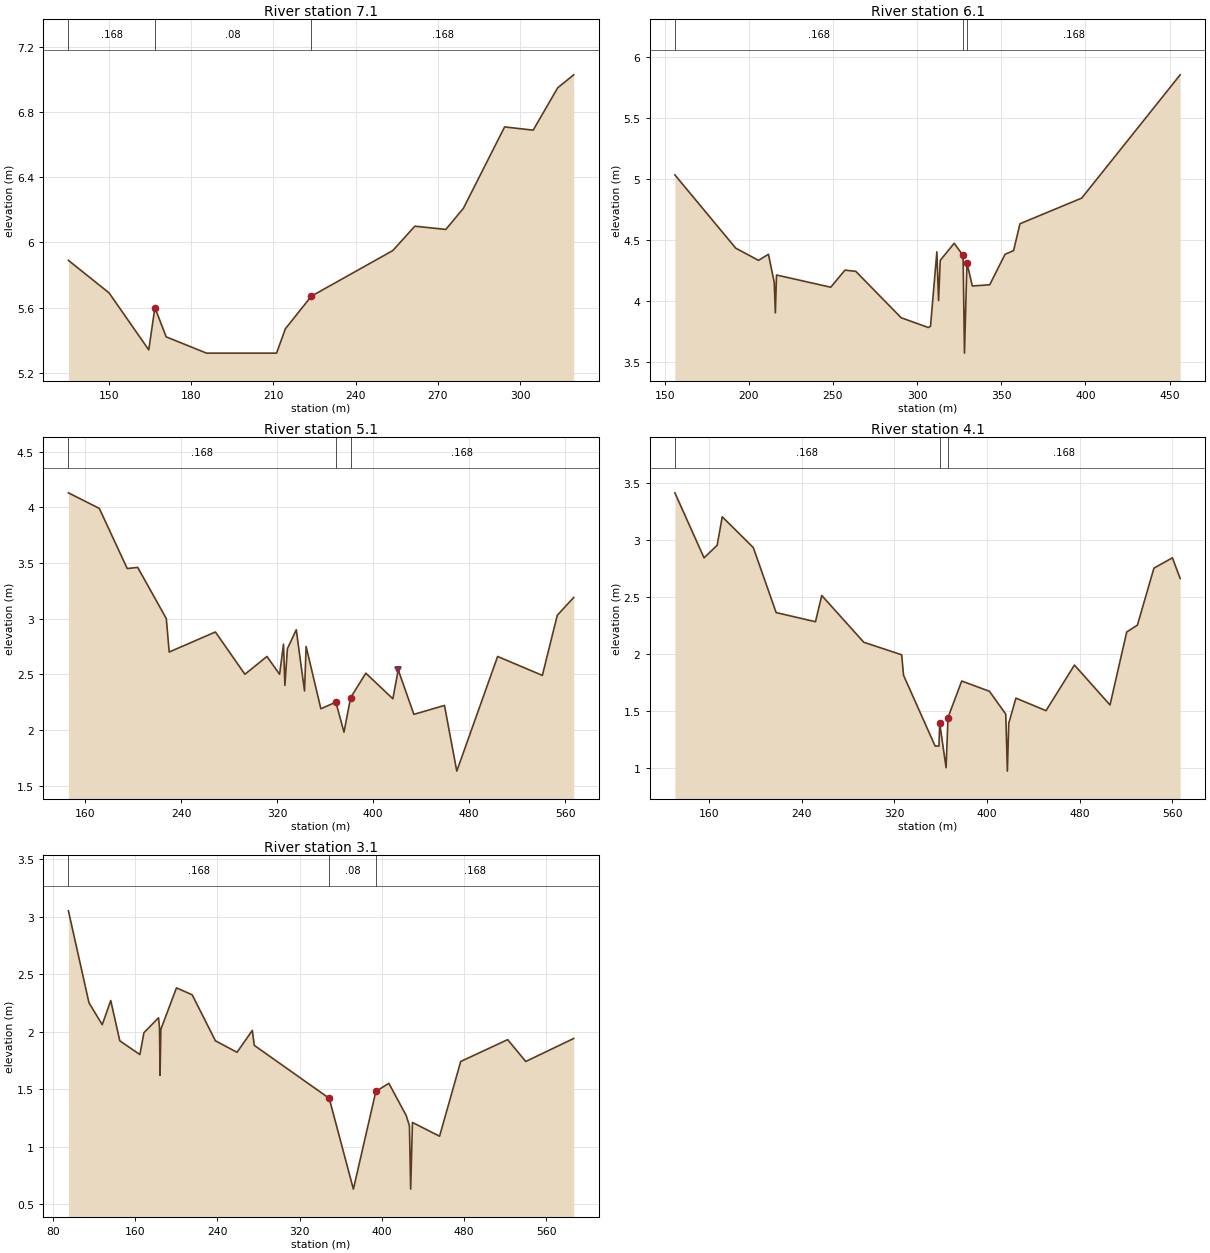
Type RM Length L Ch R = 1 ,7.1     ,37.105,37.105,37.105
XS GIS Cut Line= 4
         465560.         214178.         465551.         214181.
         465533.         214193.         465376.         214280.
#Sta/Elev= 17
  135.26    5.89  150.09    5.69  164.56    5.34   166.8     5.6  170.92    5.42
  185.62    5.32  211.17    5.32  214.41    5.47  223.88    5.67  253.56    5.95
  261.62     6.1  272.92    6.08  279.33    6.21  294.36    6.71  304.77    6.69
  313.71    6.95  319.55    7.03
#Mann= 3 , 0 , 0
  135.26    .168       0   166.8     .08       0  223.88    .168       0
Bank Sta=166.8,223.88
XS Rating Curve= 0 ,0
Exp/Cntr=0.3,0.1

Type RM Length L Ch R = 1 ,6.1     ,33.425,33.425,33.425
XS GIS Cut Line= 2
         465520.         214114.         465253.         214250.
#Sta/Elev= 27
  156.11    5.03  192.25    4.43  205.79    4.33   211.7    4.38  215.13    4.15
   215.8     3.9  216.48    4.21  248.69    4.11  257.16    4.25  263.58    4.24
  290.52    3.86  306.63    3.78  307.97    3.79  311.75     4.4  312.76       4
  313.75    4.33  322.03    4.47  327.32    4.37  328.15    3.57  329.61    4.31
  332.82    4.12  343.14    4.13  352.26    4.38  357.33    4.41  361.12    4.63
  397.78    4.84  456.28    5.85
#Mann= 3 , 0 , 0
  156.11    .168       0  327.32     .08       0  329.61    .168       0
Bank Sta=327.32,329.61
XS Rating Curve= 0 ,0
Exp/Cntr=0.3,0.1

Type RM Length L Ch R = 1 ,5.1     ,32.75,32.75,32.75
XS GIS Cut Line= 4
         465519.         214041.         465517.         214042.
         465510.         214045.         465141.         214229.
#Sta/Elev= 30
  146.13    4.13  171.86    3.99  195.11    3.45  203.86    3.46  227.69       3
  230.08     2.7  268.57    2.88  293.17     2.5  311.51    2.66  322.06     2.5
  325.32    2.77  326.46     2.4  328.57    2.73  335.95     2.9  342.83    2.35
  344.15    2.75  356.45    2.19  368.93    2.25  375.71    1.98  381.22    2.29
   393.9    2.51  416.43    2.28  420.88    2.54  433.93    2.14  459.43    2.22
  469.67    1.63   503.7    2.66  540.97    2.49  553.41    3.03  567.07    3.19
#Mann= 3 , 0 , 0
  146.13    .168       0  368.93     .08       0  381.22    .168       0
Levee=0,,,-1,420.88,2.54,,
Bank Sta=368.93,381.22
XS Rating Curve= 0 ,0
Exp/Cntr=0.3,0.1

Type RM Length L Ch R = 1 ,4.1     ,27.91,27.91,27.91
XS GIS Cut Line= 5
         465508.         214011.         465503.         214013.
         465493.         214018.         465486.         214021.
         465117.         214205.
#Sta/Elev= 30
  130.54    3.41  155.71    2.84  167.03    2.95  171.41     3.2  198.25    2.93
  217.97    2.36  251.92    2.28  257.34    2.51  293.61     2.1  326.32    1.99
  327.97    1.81  355.21    1.19  358.52    1.19  359.19    1.39  364.69       1
  366.33    1.44  378.19    1.76  402.11    1.67   416.2    1.47   417.6     .97
  418.79    1.39  424.99    1.61  450.95     1.5  475.51     1.9  506.22    1.55
  520.64    2.19  529.86    2.25  544.15    2.75  560.06    2.84  566.77    2.66
#Mann= 3 , 0 , 0
  130.54    .168       0  359.19     .08       0  366.33    .168       0
Bank Sta=359.19,366.33
XS Rating Curve= 0 ,0
Exp/Cntr=0.3,0.1

Type RM Length L Ch R = 1 ,3.1     ,112,111.4,103.5
XS GIS Cut Line= 3
         465529.         213952.         465522.         213950.
         465091.         214169.
#Sta/Elev= 30
   95.17    3.05  115.17    2.25  128.06    2.06  136.33    2.27  145.14    1.92
  164.67     1.8  168.59    1.99   182.8    2.12  183.79    2.03  184.28    1.62
  185.09    2.02  200.25    2.38  215.54    2.32  238.12    1.92  259.15    1.82
  274.03    2.01  275.96    1.88  348.82    1.42  372.35     .63  394.21    1.48
  406.86    1.55  423.72    1.27  426.87    1.18  428.06     .63   429.8    1.21
  456.17    1.09  476.74    1.74  522.41    1.93  540.02    1.74  586.63    1.94
#Mann= 3 , 0 , 0
   95.17    .168       0  348.82     .08       0  394.21    .168       0
Bank Sta=348.82,394.21
XS Rating Curve= 0 ,0
Exp/Cntr=0.3,0.1

--- Lucky_global_v2.g04 (geometry) ---

Geom Title=Reference
Program Version=4.10

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
River Reach=lucky           ,lucky
Reach XY= 22
         465815.         214289.         465787.         214267.
         465768.         214255.         465733.         214251.
         465687.         214255.         465657.         214253.
         465613.         214245.         465594.         214236.
         465580.         214219.         465559.         214155.
         465540.         214098.         465539.         214090.
         465528.         213991.         465539.         213947.
         465551.         213907.         465558.         213883.
         465565.         213850.         465564.         213827.
         465559.         213798.         465547.         213784.
         465498.         213762.         465486.         213754.

River Reach=Fossé_RD        ,Fossé_RD

--- Lucky_global_v2.g05 (geometry) ---

Geom Title=Sensibilite_cd
Program Version=4.10

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
River Reach=lucky           ,lucky

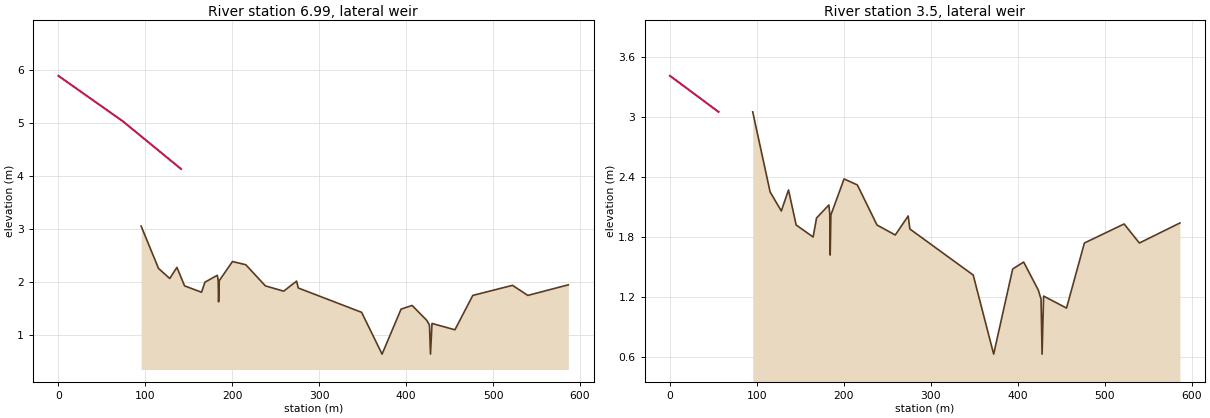
Type RM Length L Ch R = 6 ,6.99    ,,,
Lateral Weir Pos= 3
Lateral Weir End=Fossé_RD        ,Fossé_RD        ,7.1     ,
Lateral Weir Distance=0
Lateral Weir TW Multiple XS=-1
Lateral Weir WD=5
Lateral Weir Coef=1
Lateral Weir WSCriteria=-1
Lateral Weir Flap Gates= 0
Lateral Weir Hagers EQN= 0 ,,,,,
Lateral Weir SS=0.05,0.05,
Lateral Weir Type= 0
Lateral Weir Connection Pos and Dist= 0 ,0
Lateral Weir SE= 3
       0    5.89   74.21    5.03  141.05    4.13
Lateral Weir HW RS Station=6       ,74.21
Lateral Weir HW RS Station=5       ,141.05
Lateral Weir HW RS Station=4       ,173.81
Lateral Weir HW RS Station=3       ,229.63
Lateral Weir TW RS Station=7.1     ,0
Lateral Weir TW RS Station=6.1     ,74.21
Lateral Weir TW RS Station=5.1     ,141.06
Lateral Weir TW RS Station=4.1     ,173.81
Lateral Weir TW RS Station=3.1     ,229.63
LW Div RC= 0 ,False,

Type RM Length L Ch R = 6 ,3.5     ,,,
Lateral Weir Pos= 3
Lateral Weir End=Fossé_RD        ,Fossé_RD        ,4.1     ,
Lateral Weir Distance=0
Lateral Weir TW Multiple XS=0
Lateral Weir WD=5
Lateral Weir Coef=1
Lateral Weir WSCriteria=-1
Lateral Weir Flap Gates= 0
Lateral Weir Hagers EQN= 0 ,,,,,
Lateral Weir SS=0.05,0.05,
Lateral Weir Type= 0
Lateral Weir Connection Pos and Dist= 0 ,
Lateral Weir SE= 2
       0    3.41   55.82    3.05
Lateral Weir HW RS Station=4       ,0
Lateral Weir TW RS Station=4.1     ,0
LW Div RC= 0 ,False,

River Reach=Fossé_RD        ,Fossé_RD

--- Lucky_global_v2.g06 (geometry) ---

Geom Title=cd_faible
Program Version=4.10

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
River Reach=lucky           ,lucky

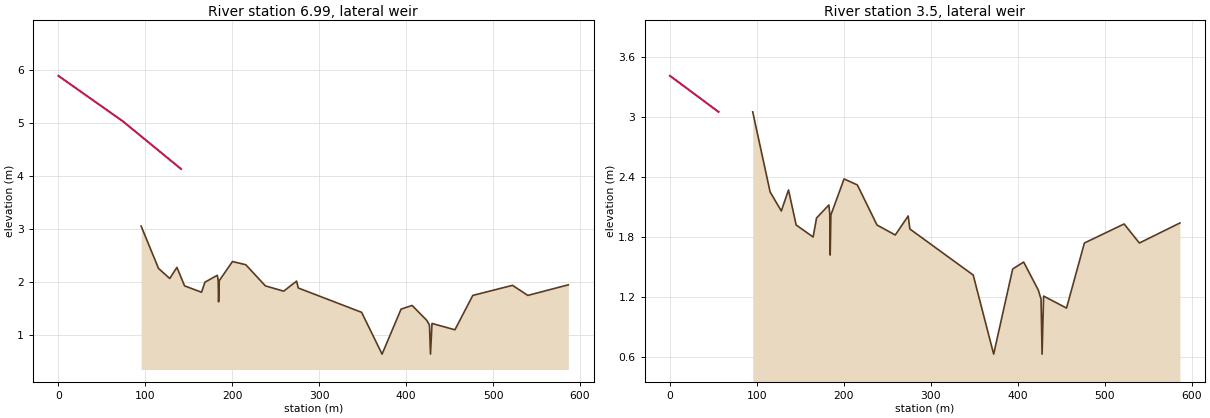
Type RM Length L Ch R = 6 ,6.99    ,,,
Lateral Weir Pos= 3
Lateral Weir End=Fossé_RD        ,Fossé_RD        ,7.1     ,
Lateral Weir Distance=0
Lateral Weir TW Multiple XS=-1
Lateral Weir WD=5
Lateral Weir Coef=0.5
Lateral Weir WSCriteria=-1
Lateral Weir Flap Gates= 0
Lateral Weir Hagers EQN= 0 ,,,,,
Lateral Weir SS=0.05,0.05,
Lateral Weir Type= 0
Lateral Weir Connection Pos and Dist= 0 ,0
Lateral Weir SE= 3
       0    5.89   74.21    5.03  141.05    4.13
Lateral Weir HW RS Station=6       ,74.21
Lateral Weir HW RS Station=5       ,141.05
Lateral Weir HW RS Station=4       ,173.81
Lateral Weir HW RS Station=3       ,229.63
Lateral Weir TW RS Station=7.1     ,0
Lateral Weir TW RS Station=6.1     ,74.21
Lateral Weir TW RS Station=5.1     ,141.06
Lateral Weir TW RS Station=4.1     ,173.81
Lateral Weir TW RS Station=3.1     ,229.63
LW Div RC= 0 ,False,

Type RM Length L Ch R = 6 ,3.5     ,,,
Lateral Weir Pos= 3
Lateral Weir End=Fossé_RD        ,Fossé_RD        ,4.1     ,
Lateral Weir Distance=0
Lateral Weir TW Multiple XS=0
Lateral Weir WD=5
Lateral Weir Coef=0.5
Lateral Weir WSCriteria=-1
Lateral Weir Flap Gates= 0
Lateral Weir Hagers EQN= 0 ,,,,,
Lateral Weir SS=0.05,0.05,
Lateral Weir Type= 0
Lateral Weir Connection Pos and Dist= 0 ,
Lateral Weir SE= 2
       0    3.41   55.82    3.05
Lateral Weir HW RS Station=4       ,0
Lateral Weir TW RS Station=4.1     ,0
LW Div RC= 0 ,False,

River Reach=Fossé_RD        ,Fossé_RD